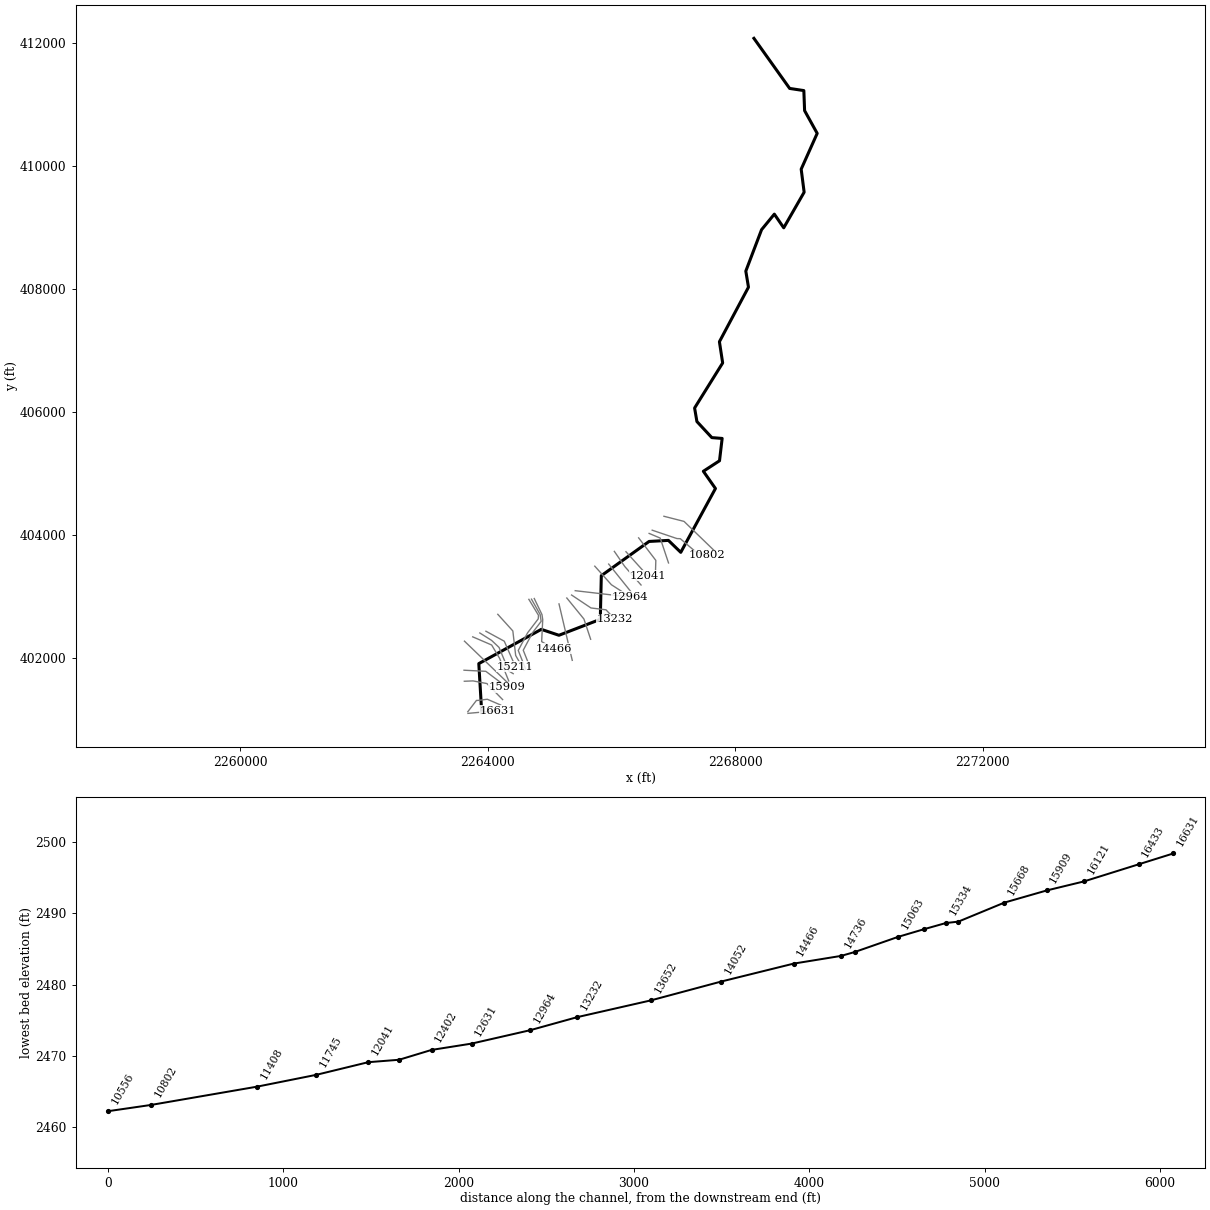
--- COCHRNCK.prj (project) ---

Proj Title=COCHRNCK
Current Plan=p01
Default Exp/Contr=0,0
English Units
Geom File=g01
Flow File=f01
Plan File=p01
Background Map Layer=Inundation Boundary (01pct Value_0)
BEGIN DESCRIPTION:
----------MODEL BY WOOD PLC 2021----------
Stream Name: Cochran Run
Flood Zone: Enhanced Approximate
Pocahontas County, WV
HEC-RAS Version: RAS 6.1
Vertical Datum: NAVD88
Projection: NAD 1983 StatePlane West Virginia S FIPS 4702 (US Feet)
Terrain: 1-meter LIDAR (FEMA Region III 3DEP collected 2016-2018)
Land Use: 2019 NLCD
Hydrologic Method:
WV SIR2010-5033 regression equations
Model Notes:
Normal depth tie in to Laurel Creek
END DESCRIPTION:
DSS Export Rating Curves= 0
DSS Export Rating Curve Sorted= 0
DSS Export Volume Flow Curves= 0
DXF OffsetX= 0
DXF OffsetY= 0
DXF ScaleX= 0
DXF ScaleY= 0

--- COCHRNCK.p01 (plan) ---

Plan Title=Floodplain
Program Version=6.10
Short Identifier=Floodplain
Geom File=g01
Flow File=f01
Subcritical Flow
K Sum by GR= 0
Std Step Tol= 0.01
Critical Tol= 0.01
Num of Std Step Trials= 20
Max Error Tol= 0.3
Flow Tol Ratio= 0.001
Split Flow NTrial= 30
Split Flow Tol= 0.02
Split Flow Ratio= 0.02
Log Output Level= 0
Friction Slope Method= 1
Unsteady Friction Slope Method= 2
Unsteady Bridges Friction Slope Method= 1
Parabolic Critical Depth
Global Vel Dist= 0 , 0 , 0
Global Log Level= 0
CheckData=True
Encroach Param=-1 ,0,0, 0
Mapping Interval=1HOUR
Computation Time Step Use Courant=        0
Computation Time Step Use Time Series=    0
Computation Time Step Count To Double=0
Computation Time Step Max Doubling=0
Computation Time Step Max Halving=0
Computation Time Step Residence Courant=0
Run HTab= 0
Run UNet= 0
Run Sediment= 0
Run PostProcess= 0
Run WQNet= 0
Run RASMapper=-1
UNET Theta= 0
UNET Theta Warmup= 0
UNET ZTol= 0
UNET ZSATol= 0
UNET MxIter= 0
UNET Max Iter WO Improvement= 0
UNET MaxInSteps= 0
UNET DtIC= 0
UNET DtMin= 0
UNET MaxCRTS= 0
UNET WFStab= 0
UNET SFStab= 0
UNET WFX= 1
UNET SFX= 1
UNET Gravity=32.174
UNET 1D Methodology=Finite Difference
UNET DSS MLevel= 1
UNET Pardiso=0
UNET DZMax Abort= 0
UNET Use Existing IB Tables= 0
UNET Froude Reduction=False
UNET Froude Limit= 0
UNET Froude Power= 0
UNET D1 Cores= 0
UNET WindReference=Eulerian
UNET WindDragFormulation=Hsu (1988)
UNET D2 Coriolis=0
UNET D2 Cores= 0
UNET D2 Theta= 1
UNET D2 Theta Warmup= 1
UNET D2 Z Tol= 0.01
UNET D2 Volume Tol= 0.01
UNET D2 Max Iterations= 20
UNET D2 Equation= 0
UNET D2 RampUpFraction=0.1
UNET D2 TimeSlices= 1
UNET D2 Turbulence Formulation=Non-Conservative (original)
UNET D2 Eddy Viscosity=0.3
UNET D2 Transverse Eddy Viscosity=0.1
UNET D2 Smagorinsky Mixing=0
UNET D2 BCVolumeCheck=0
UNET D2 Cores=0
UNET D2 SolverType=PARDISO (Direct)
UNET D2 Minimum Iterations= 2147483647
UNET D2 Maximum Iterations= 2147483647
UNET D2 Restart Number= 10
UNET D2 Relaxation Coeff=1.3
UNET D2 SOR Precondition Iterations= 10
UNET D2 ILUT Maximum Fill= 8
UNET D2 ILUT Tolerance=1E-08
UNET D1D2 MaxIter= 0
UNET D1D2 ZTol=0.01
UNET D1D2 QTol=0.1
UNET D1D2 MinQTol=1
Write IC File= 0
Write IC File at Fixed DateTime=0
Write IC File at Sim End=0
Echo Input=False
Echo Parameters=False
Echo Output=False
Write Detailed= 0
HDF Write Warmup=0
HDF Write Time Slices=0
HDF Flush=0
HDF Compression= 1
HDF Chunk Size= 1
HDF Spatial Parts= 1
HDF Use Max Rows=0
HDF Fixed Rows= 1
Calibration Method= 0
Calibration Iterations= 20
Calibration Max Change=0.05
Calibration Tolerance=0.2
Calibration Maximum=1.5
Calibration Minimum=0.5
Calibration Optimization Method= 1
WQ AD Non Conservative
WQ ULTIMATE=-1
WQ Max Comp Step=1HOUR
WQ Output Interval=15MIN
WQ Output Selected Increments= 0
WQ Output face flow=0
WQ Output face velocity=0
WQ Output face area=0
WQ Output face dispersion=0
WQ Output cell volume=0
WQ Output cell surface area=0
WQ Output cell continuity=0
WQ Output cumulative cell continuity=0
WQ Output face conc=0
WQ Output face dconc_dx=0
WQ Output face courant=0
WQ Output face peclet=0
WQ Output face adv mass=0
WQ Output face disp mass=0
WQ Output cell mass=0
WQ Output cell source sink temp=0
WQ Output nsm pathways=0
WQ Output nsm derived pathways=0
WQ Create Restart=0
WQ Fixed Restart=0
WQ System Summary=0
WQ Write To DSS=0
Sorting and Armoring Iterations= 10
XS Update Threshold= 0.02
Bed Roughness Predictor= 0
Hydraulics Update Threshold= 0.02
Energy Slope Method= 1
Volume Change Method= 1
Sediment Retention Method= 0
Sediment TS Multiplier= 1
Warm Up Method= 0
XS Weighting Method= 0
Number of US Weighted Cross Sections= 1
Number of DS Weighted Cross Sections= 1
Upstream XS Weight=0
Main XS Weight=1
Downstream XS Weight=0
Number of DS XS's Weighted with US Boundary= 1
Upstream Boundary Weight= 1
Weight of XSs Associated with US Boundary= 0
Number of US XS's Weighted with DS Boundary= 1
Downstream Boundary Weight= 0.5
Weight of XSs Associated with DS Boundary= 0.5
Percentile Method= 0
Sediment Output Level= 3
Mass or Volume Output= 0
Output Increment Type= 1
Profile and TS Output Increment= 1
Transport Output Increment 1
XS Output Flag= 0
XS Output Increment= 10
Read HDF5 Sediment Hotstart= 0
Sediment Hotstart Type= 0
Write Gradation File= 0
Read Gradation Hotstart= 0
Write HDF5 File= 1
Write Binary Output= 1
Write DSS Sediment File= 0
DSS Sediment Output Type= 1
SV Curve= 0
Specific Gage Flag= 0
Subcell Erosion Methods= 0
Subcell Deposition Methods= 0
Advection Scheme= 1
Matrix Solver= 0
Implicit Weighting Factor= 1
Maximum Outer Loop Convergence Iterations= 5
Convergence Maximum Absolute= 0.001
Convergence RMSE= 0.0001
Grain Fractions Max Abs Error= 0.001
Max Subgrid Regions= 1
Max Subgrid Length Scale= 3.402823E+38
Initial Layer Thickness= 3.402823E+38
Min Layer Thickness= 3.402823E+38
Max Layer Thickness= 3.402823E+38
Number of Layers= 5

--- COCHRNCK.f01 (steady flow) ---

Flow Title=Flow
Program Version=6.10
Number of Profiles= 6
Profile Names=01pct,10pct,04pct,02pct,0_2pct,01plus
River Rch & RM=COCHRNCK,Main            ,16631
     819     439     579     695    1140    1210
River Rch & RM=COCHRNCK,Main            ,15063
    1010     547     719     861    1400    1500
River Rch & RM=COCHRNCK,Main            ,12631
    1190     644     845    1010    1630    1750
River Rch & RM=COCHRNCK,Main            ,9323
    1340     729     954    1140    1840    1970
River Rch & RM=COCHRNCK,Main            ,8732
    1600     877    1140    1360    2190    2360
River Rch & RM=COCHRNCK,Main            ,5998
    1810     997    1300    1540    2470    2670
Boundary for River Rch & Prof#=COCHRNCK,Main            , 1
Up Type= 0
Dn Type= 3
Dn Slope=0.00737
Boundary for River Rch & Prof#=COCHRNCK,Main            , 2
Up Type= 0
Dn Type= 3
Dn Slope=0.00737
Boundary for River Rch & Prof#=COCHRNCK,Main            , 3
Up Type= 0
Dn Type= 3
Dn Slope=0.00737
Boundary for River Rch & Prof#=COCHRNCK,Main            , 4
Up Type= 0
Dn Type= 3
Dn Slope=0.00737
Boundary for River Rch & Prof#=COCHRNCK,Main            , 5
Up Type= 0
Dn Type= 3
Dn Slope=0.00737
Boundary for River Rch & Prof#=COCHRNCK,Main            , 6
Up Type= 0
Dn Type= 3
Dn Slope=0.00737
DSS Import GetInterval= 0
DSS Import GetPeak= 0
DSS Import FillOption= 0

--- COCHRNCK.g01 (geometry) ---

Geom Title=Geometry
Program Version=6.10

River Reach=COCHRNCK        ,Main
Reach XY= 30
     2263902.394      401122.213     2263855.069      401916.334
2264865.31139944402472.643856488      2265150.51      402376.595
      2265818.91      402635.046     2265835.622      403343.825
     2266607.958      403899.838     2266920.425      403916.855
2267119.97309045403722.949904851     2267680.717      404759.186
     2267485.381      405039.1192267746.31384719405209.614304489
     2267789.003       405572.03     2267622.055      405585.508
     2267381.119      405846.133     2267343.648       406066.13
     2267797.346      406797.533     2267744.864      407142.398
     2268214.545      408027.534     2268171.559      408288.586
     2268426.239      408961.128     2268632.688      409213.472
     2268784.548        408991.7     2269114.475      409569.464
     2269066.676      409943.757     2269325.498      410524.846
     2269121.898      410893.764     2269109.666       411219.58
 2268880.3667066411254.350111417     2268302.756      412067.711

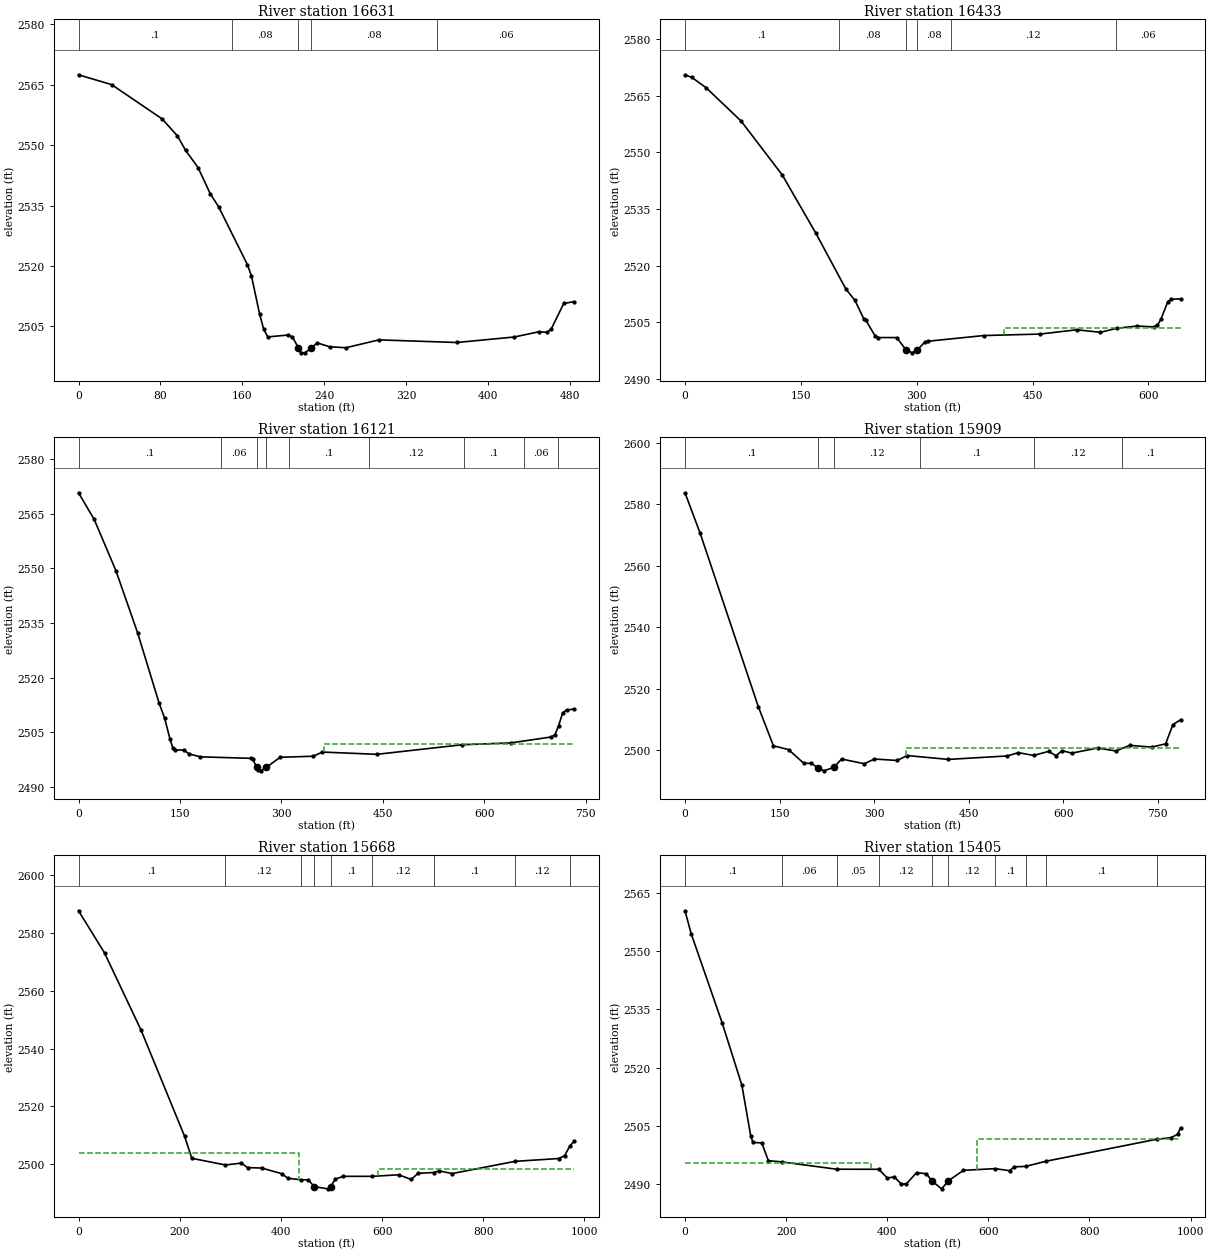
Type RM Length L Ch R = 1 ,16631   ,198.4,198.4,198.4
XS GIS Cut Line= 2
2263679.90629021401108.5299566382264162.24753892401152.717100784
#Sta/Elev= 30
       0 2567.49    32.4 2565.04    81.8 2556.51    96.7 2552.29   104.7  2548.7
   116.8 2544.44   128.8 2537.92     137 2534.65     165 2520.34     169 2517.53
     177 2508.04     181 2504.23     185 2502.36   205.1 2502.83   209.1 2502.33
214.93352499.625   217.2 2498.45   221.2  2498.4  227.482499.595   233.2 2500.88
   245.3 2499.91   261.4 2499.67   293.5 2501.62   369.8 2500.97     426 2502.34
   450.1 2503.65   458.2 2503.48   462.2 2504.44   474.2 2510.66   484.4 2511.13
#Mann= 5 ,-1,0
       0      .1       0     150     .08       0214.9335    .045       0
  227.48     .08       0     350     .06       0
Bank Sta=214.9335,227.48
XS Rating Curve= 0 ,0
Exp/Cntr=0.3,0.1

Type RM Length L Ch R = 1 ,16433   ,314.7,311.7,307.2
XS GIS Cut Line= 5
2263677.39293573401135.5338825392263817.60297954401319.507287501
2263840.22712625401318.7923027972263992.48497429401337.855430298
2264207.52726684401244.731783986
#Sta/Elev= 30
       0 2570.52     8.9 2569.81    27.2 2567.12    72.5  2558.3   125.9    2544
   169.6  2528.5   208.3 2513.77   220.1 2510.75   231.3 2505.95   233.9  2505.6
   245.9 2501.45   249.9 2500.92   274.1 2500.91   286.1 2497.69   294.2 2496.87
  300.842497.646   310.3 2499.68   314.4 2499.94   386.9 2501.45   459.4 2501.84
   507.3 2502.98   537.8 2502.31   559.6  2503.4   585.8 2503.97   607.6 2503.72
   611.5 2504.15   616.3 2505.81     625 2510.38   629.4 2511.06   641.7 2511.16
#Mann= 6 ,-1,0
       0      .1       0     200     .08       0   286.1    .045       0
  300.84     .08       0  343.95     .12       0  557.39     .06       0
#XS Ineff= 2 , 0
                          413.52          2503.5
Permanent Ineff=
       F       F
Bank Sta=286.1,300.84
XS Rating Curve= 0 ,0
Exp/Cntr(USF)=0,0
Exp/Cntr=0.3,0.1

Type RM Length L Ch R = 1 ,16121   ,209.4,212.8,208.1
XS GIS Cut Line= 4
2263620.97398953401630.1271074992263762.00194598401635.630678257
2263985.98797694401592.5845029252264240.02545695401332.649529136
#Sta/Elev= 30
       0  2570.7    23.2 2563.39    55.2 2549.39    87.3 2532.35   119.3 2512.94
   127.3 2508.92   135.3 2503.13   139.3 2500.86   143.3 2500.19   155.6 2500.16
   163.7  2499.1     180 2498.31   254.4  2497.9   257.4 2497.65  263.332495.522
   265.5 2494.61   269.6 2494.47   277.8 2495.44   298.1 2498.19     347 2498.47
   360.3 2499.62   441.1    2499   566.9 2501.62   639.1 2502.13   698.6 2503.75
   704.3 2504.37   709.6 2506.77   715.7 2510.37   721.4 2511.16   732.7  2511.4
#Mann= 9 ,-1,0
       0      .1       0  211.14     .06       0  263.33    .045       0
   277.8     .06       0  311.14      .1       0  429.22     .12       0
  569.22      .1       0  659.22     .06       0  709.22      .1       0
#XS Ineff= 2 , 0
                          362.49         2501.94
Permanent Ineff=
       F       F
Bank Sta=263.33,277.8
XS Rating Curve= 0 ,0
Exp/Cntr=0.3,0.1

Type RM Length L Ch R = 1 ,15909   ,249.3,240.8,225
XS GIS Cut Line= 3
 2263616.0316793401809.2858533742263968.60811323401791.293398713
2264314.00146372401529.635139311
#Sta/Elev= 30
       0 2583.73    24.2 2570.49   116.3 2514.12   140.3 2501.36   164.4  2500.1
   188.4 2495.66   200.4 2495.65211.34712494.148   220.4  2493.2236.1471 2494.36
   248.5 2497.04   284.5 2495.52   300.5 2497.05   336.6 2496.57   352.6 2498.18
   417.7 2496.92   511.3 2498.05   528.8 2499.13   553.2 2498.21   576.9 2499.54
   588.4 2498.13   598.4 2499.77   613.4 2498.96   654.6 2500.64   683.7 2499.67
   705.4  2501.5   740.7 2500.93   762.5 2501.99     774 2508.24   786.3 2509.83
#Mann= 6 ,-1,0
       0      .1       0211.3471    .045       0236.1471     .12       0
  373.04      .1       0  553.04     .12       0  693.04      .1       0
#XS Ineff= 2 , 0
                             350         2500.63
Permanent Ineff=
       F       F
Bank Sta=211.3471,236.1471
XS Rating Curve= 0 ,0
Exp/Cntr(USF)=0,0
Exp/Cntr=0.3,0.1

Type RM Length L Ch R = 1 ,15668   ,265.4,262.6,252.4
XS GIS Cut Line= 2
 2263623.2989163 402280.92556604 2264327.7619163 401600.03756604
#Sta/Elev= 30
       0 2587.67    51.4  2573.1   123.6  2546.4   209.8 2509.62   223.9 2502.06
   290.5 2499.75   321.9  2500.4   334.2 2498.86   362.5 2498.68   401.8 2496.73
     414 2495.15   440.7 2494.62   454.3 2494.62   465.8 2492.29   492.7  2491.5
   498.3 2492.25   507.5 2494.85   523.4 2495.83   580.4 2495.82   632.8 2496.36
   657.7 2494.75   670.9 2496.85   701.8 2497.15   713.3 2497.69   738.8 2496.79
     863 2501.01   949.3 2501.99   960.8 2502.97   970.7 2506.16   979.7    2508
#Mann= 9 ,-1,0
       0      .1       0   290.5     .12       0   440.7      .1       0
   465.8    .045       0   498.3      .1       0   580.4     .12       0
   701.8      .1       0     863     .12       0   970.7     .07       0
#XS Ineff= 2 , 0
       0     436 2503.75  592.32       0 2498.33
Permanent Ineff=
       F       F
Bank Sta=465.8,498.3
XS Rating Curve= 0 ,0
Exp/Cntr=0.3,0.1

Type RM Length L Ch R = 1 ,15405   ,74.2,71.5,69
XS GIS Cut Line= 4
2263756.84877759402351.0422187312264062.64284405402218.806946748
2264190.15542775402003.9246297762264338.92010873401635.554943538
#Sta/Elev= 30
       0 2560.39    12.3 2554.48    73.4 2531.59   112.6 2515.47     130 2502.48
   134.4 2500.76   151.8 2500.66   164.9 2496.08     191 2495.77     300 2493.88
   383.2 2493.86   400.2 2491.63   414.1 2491.89   428.1 2490.01   438.1 2490.13
   458.1 2493.01   477.3 2492.71   489.32490.757   507.7 2488.83   521.1 2490.92
   550.8 2493.59   613.3 2494.03     642  2493.5   651.2 2494.49   673.9 2494.61
   714.6 2495.95   933.9 2501.62   961.3 2501.99   974.2 2502.88   980.3 2504.53
#Mann= 10 ,-1,0
       0      .1       0     191     .06       0     300     .05       0
   383.2     .12       0   489.3    .045       0   521.1     .12       0
   613.3      .1       0   673.9     .07       0   714.6      .1       0
   933.9     .07       0
#XS Ineff= 2 , 0
       0  368.84 2495.55     577       0 2501.53
Permanent Ineff=
       F       F
Bank Sta=489.3,521.1
XS Rating Curve= 0 ,0
Exp/Cntr(USF)=0,0
Exp/Cntr=0.3,0.1

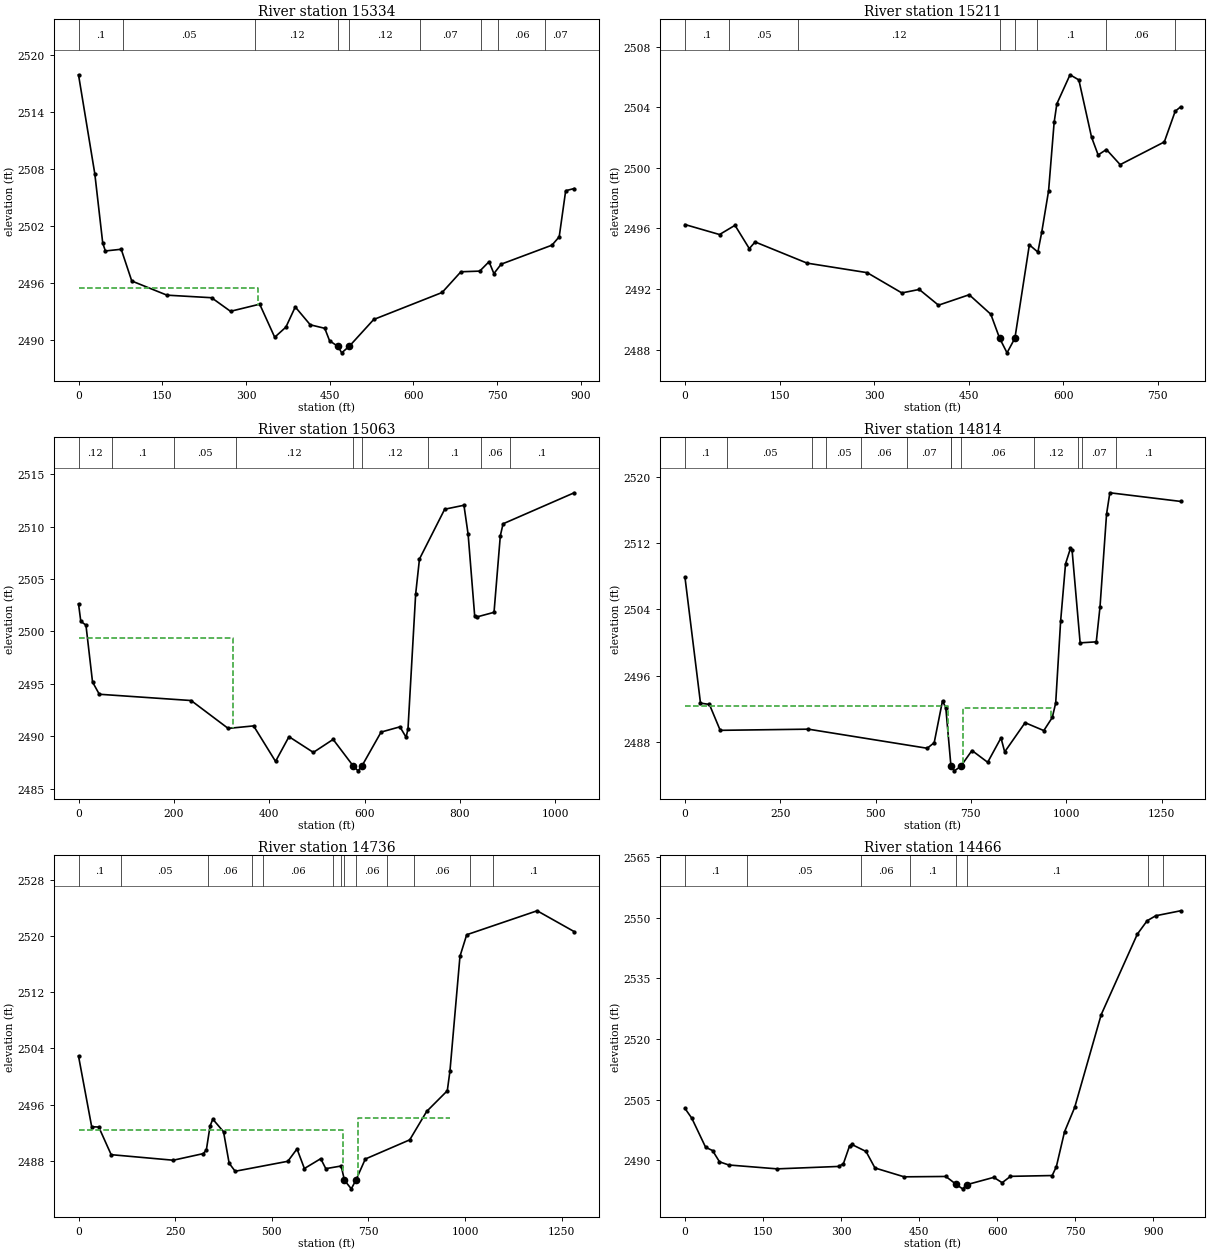
Type RM Length L Ch R = 1 ,15334   ,122.7,122.6,124.3
XS GIS Cut Line= 5
2263871.52878452402413.8020838522264062.58755696402293.014273373
2264182.43858006 402179.341138062264340.91234293401796.297487822
2264410.96959045401753.262321486
#Sta/Elev= 30
       0 2517.89    29.2 2507.47    43.4 2500.18    48.1 2499.35    76.5 2499.53
    95.4 2496.19   158.4  2494.7   238.4 2494.43   272.3    2493   324.6 2493.75
   351.5 2490.27   371.6 2491.34   388.3 2493.46   415.2 2491.58   441.2 2491.21
   449.8  2489.9 464.8572489.303   471.5 2488.63 485.3572489.336   528.9 2492.14
   651.4 2494.98   685.1 2497.16   718.8 2497.23   735.5 2498.22   744.2 2496.97
   757.2 2497.96   848.2 2499.96   861.2 2500.84   872.8 2505.69     888 2505.92
#Mann= 9 ,-1,0
       0      .1       0      80     .05       0  316.04     .12       0
 464.857    .045       0 485.357     .12       0  611.22     .07       0
  721.22      .1       0  751.22     .06       0  835.75     .07       0
#XS Ineff= 2 , 0
          320.79 2495.43
Permanent Ineff=
       F       F
Bank Sta=464.857,485.357
XS Rating Curve= 0 ,0
Exp/Cntr(USF)=0,0
Exp/Cntr=0.3,0.1

Type RM Length L Ch R = 1 ,15211   ,154.9,148.3,150.2
XS GIS Cut Line= 3
2263970.55042249402441.9539682192264266.89911238402280.201894454
2264446.36126722401869.328013651
#Sta/Elev= 30
       0 2496.26    54.8  2495.6    79.3 2496.21     102 2494.67   111.2 2495.11
   193.6 2493.71   288.9 2493.08   343.9 2491.74   371.5 2491.97     402 2490.93
   450.7 2491.62     485 2490.33   498.9 2488.75   510.7 2487.78   523.2 2488.75
   546.1 2494.92   559.6 2494.44   565.8 2495.77   576.6 2498.49   585.4 2503.01
   589.7 2504.24   610.6 2506.16   624.6 2505.82   644.7 2502.04   655.2 2500.86
   668.3 2501.22   690.1 2500.22   760.1 2501.72   777.4 2503.75     786 2504.04
#Mann= 8 ,-1,0
       0      .1       0      70     .05       0     180     .12       0
   498.9    .045       0   523.2     .12       0  557.62      .1       0
  667.62     .06       0  777.62      .1       0
Bank Sta=498.9,523.2
XS Rating Curve= 0 ,0
Exp/Cntr(USF)=0,0
Exp/Cntr=0.3,0.1

Type RM Length L Ch R = 1 ,15063   ,249.2,249.2,249.2
BEGIN DESCRIPTION:
structure xs 4
END DESCRIPTION:
XS GIS Cut Line= 4
2264162.16080041402716.749140619 2264405.4566223402446.485955127
2264451.17299194402048.6299815362264587.08652329401808.927935335
#Sta/Elev= 30
       0 2502.64     4.8 2500.97    15.6 2500.61    29.4 2495.18    43.6 2494.01
   236.2 2493.41   313.9 2490.75   367.3 2490.99   413.3  2487.6   441.5 2489.96
   492.6 2488.46   534.1  2489.7   575.8 2487.19   586.4  2486.7   594.8 2487.19
   634.7  2490.4   674.2  2490.9   687.1 2489.91   691.1 2490.68   707.2 2503.57
   715.2 2506.92   768.1 2511.67   808.5 2512.05   817.3 2509.26     831  2501.5
   834.9 2501.38   871.6 2501.83   884.8 2509.14   890.6 2510.28  1039.7 2513.24
#Mann= 9 ,-1,0
       0     .12       0      70      .1       0     200     .05       0
     330     .12       0   575.8    .045       0   594.8     .12       0
  733.64      .1       0  844.12     .06       0  904.12      .1       0
#XS Ineff= 2 , 0
          324.92 2499.35
Permanent Ineff=
       F       F
Bank Sta=575.8,594.8
XS Rating Curve= 0 ,0
Exp/Cntr(USF)=0,0
Exp/Cntr=0.5,0.3

Type RM Length L Ch R = 1 ,14814   ,77.3,77.3,77.3
BEGIN DESCRIPTION:
structure xs 3; 5.8 ft between structure and xs
END DESCRIPTION:
XS GIS Cut Line= 6
2264664.27597366 402960.111622072264820.28630889402700.279159352
2264815.90208801402642.9451681062264643.57263341402415.843414081
2264492.52439321402130.0859682172264613.88715693401824.586597475
#Sta/Elev= 30
       0 2507.87    40.7 2492.72    64.1 2492.56    92.4 2489.44   323.7 2489.58
   635.4 2487.28   653.7 2487.95   675.5    2493   684.2 2492.14697.72852485.087
   706.8 2484.56723.38462485.107   752.8 2487.01     794 2485.59   828.9 2488.53
   838.6 2486.84   892.1 2490.36   941.2 2489.41   963.5 2490.99   972.4 2492.74
   985.3 2502.58   998.2  2509.5  1011.1 2511.36  1015.4 2511.12  1036.5 2499.98
  1078.8  2500.1  1088.6  2504.3  1105.8 2515.49  1114.4 2518.06  1300.1 2517.02
#Mann= 13 ,-1,0
       0      .1       0     110     .05       0  333.07     .06       0
  370.57     .05       0  460.57     .06       0  581.71     .07       0
  696.99     .06       0697.7285    .045       0723.3846     .06       0
  916.68     .12       0 1031.38      .1       0 1041.38     .07       0
 1131.38      .1       0
#XS Ineff= 2 ,-1
       0     691  2492.4     730   960.1  2492.1
Permanent Ineff=
       F       F
Bank Sta=697.7285,723.3846
XS Rating Curve= 0 ,0
Exp/Cntr(USF)=0,0
Exp/Cntr=0.5,0.3

Type RM Length L Ch R = 1 ,14736   ,253.2,270,275.9
BEGIN DESCRIPTION:
structure xs 2; 13.9 ft between structure and xs
END DESCRIPTION:
XS GIS Cut Line= 6
 2264706.6607231402962.8930737132264846.71201873402713.492014274
2264863.12897086 402602.277574542264724.49867122402419.415631925
2264573.45043102402133.6581860612264694.81319474401828.158815319
#Sta/Elev= 30
       0 2502.91    34.1 2492.85    52.4 2492.81    84.5 2488.88   245.1 2488.09
   322.8 2489.03   330.8 2489.55   340.4 2492.95   347.5 2493.93   375.3 2492.14
   389.8 2487.66   405.4 2486.52   541.7 2487.94   565.4  2489.7   584.5 2486.91
   626.8 2488.31   639.9 2486.89   679.7 2487.27688.18982485.233   705.9 2484.02
717.71142485.246   742.1 2488.26   857.1 2490.99   900.9 2495.03   954.3 2497.97
   961.2 2500.79   987.1  2517.1  1004.5 2520.16  1186.8 2523.57  1282.6 2520.61
#Mann= 13 ,-1,0
       0      .1       0     110     .05       0  336.03     .06       0
  448.45      .1       0  478.45     .06       0  658.93     .07       0
  679.43     .06       0688.1898    .045       0717.7114     .06       0
  799.13      .1       0  869.13     .06       0 1013.83     .07       0
 1073.83      .1       0
#XS Ineff= 2 ,-1
       0     684  2492.4     722     962  2494.1
Permanent Ineff=
       F       F
Bank Sta=688.1898,717.7114
XS Rating Curve= 0 ,0
Exp/Cntr(USF)=0,0
Exp/Cntr=0.5,0.3

Type RM Length L Ch R = 1 ,14466   ,405.8,413.8,417.7
BEGIN DESCRIPTION:
structure xs 1
END DESCRIPTION:
XS GIS Cut Line= 5
2264751.61699245402973.0138322312264876.44094231 402712.39094303
2264888.56744738402630.5870112292264871.26936157402273.505097044
2265064.01946058 402161.06753929
#Sta/Elev= 30
       0 2502.82    13.1 2500.41    39.7 2493.21      53 2492.41    66.3 2489.63
    84.1 2488.84   177.2 2487.88   295.1 2488.48   304.4 2489.17   316.2 2493.56
   320.5 2493.92   347.9 2492.18     365  2488.1   421.1 2485.91   501.2    2486
521.25382484.025   533.3 2482.94541.45382483.968   593.3 2485.78   609.4 2484.46
   625.4 2486.03   705.5 2486.23   713.5 2488.41   729.2 2497.04   748.7 2503.06
   799.7 2526.03   869.1 2545.93     888 2549.25   904.5 2550.48   952.3 2551.71
#Mann= 8 ,-1,0
       0      .1       0     120     .05       0  338.97     .06       0
  431.67      .1       0521.2538    .045       0541.4538      .1       0
  889.17     .12       0  919.17      .1       0
Bank Sta=521.2538,541.4538
XS Rating Curve= 0 ,0
Exp/Cntr(USF)=0,0
Exp/Cntr=0.3,0.1

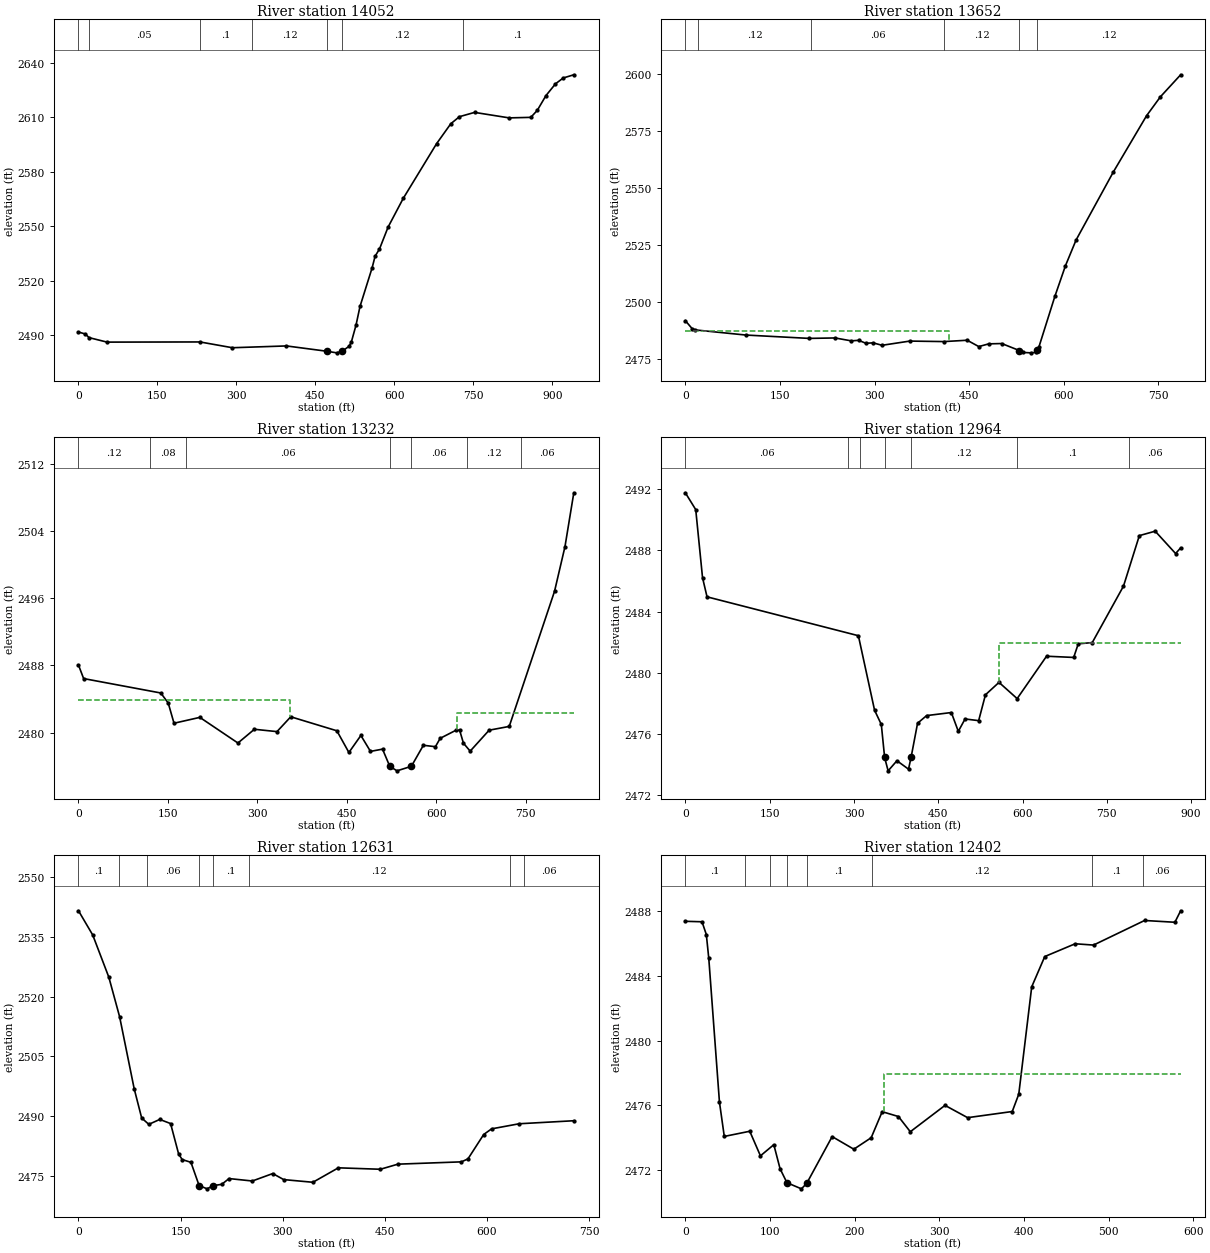
Type RM Length L Ch R = 1 ,14052   ,395.3,400.5,399.9
XS GIS Cut Line= 2
2265151.61393069      402885.9312265365.80393069      401969.591
#Sta/Elev= 30
       0 2491.86    13.1 2490.77      20 2488.79    54.2 2486.32   230.8 2486.41
   292.4 2483.23   395.1 2484.22     472 2481.29   490.5 2480.42   500.5 2481.28
   514.2 2484.02   518.4 2486.41   527.2  2495.6   534.8 2505.92   557.8 2527.15
   563.5 2533.57   571.8 2537.51   588.2  2549.6   616.9 2565.35   680.3 2595.47
   707.3 2606.43   723.7 2610.31   752.5 2612.67   818.2 2609.65   859.3 2609.94
   871.6 2613.79   888.1 2621.91   906.2 2628.38   920.9  2631.6     941 2633.36
#Mann= 7 ,-1,0
       0     .06       0      20     .05       0     230      .1       0
     330     .12       0     472    .045       0   500.5     .12       0
     730      .1       0
Bank Sta=472,500.5
XS Rating Curve= 0 ,0
Exp/Cntr=0.3,0.1

Type RM Length L Ch R = 1 ,13652   ,388.2,419.7,438.1
XS GIS Cut Line= 3
2265277.77437807402981.491037626  2265554.543751402640.471631691
2265663.27457608402311.808001333
#Sta/Elev= 30
       0 2491.89    10.7 2488.43    15.9 2487.83    95.8 2485.59   196.2 2484.12
   237.4 2484.31   263.1 2483.04   274.9 2483.27   286.3 2481.97   297.7 2482.17
   311.9 2481.09   355.9 2482.94     410 2482.72   446.9 2483.31   465.3 2480.53
   481.1 2481.72   501.7 2481.86  529.582478.802   535.4 2477.95   547.6 2477.78
   556.4 2477.99  558.142478.811   560.6 2480.31   585.9 2502.51   602.8 2516.05
   619.6  2527.3   678.6 2557.11   731.4 2581.84   753.3 2590.13   785.4 2599.79
#Mann= 6 ,-1,0
       0     .06       0      20     .12       0     200     .06       0
     410     .12       0  529.58    .045       0  558.14     .12       0
#XS Ineff= 2 , 0
          418.71 2487.41
Permanent Ineff=
       F       F
Bank Sta=529.58,558.14
XS Rating Curve= 0 ,0
Exp/Cntr(USF)=0,0
Exp/Cntr=0.3,0.1

Type RM Length L Ch R = 1 ,13232   ,271,267.9,268.8
XS GIS Cut Line= 4
2265355.07566723403029.9432359132265668.60969505402820.045978797
2265911.30339859402789.873248087  2266054.295905402637.697736678
#Sta/Elev= 30
       0 2488.05     8.6 2486.44     138 2484.72   150.5 2483.52   160.2 2481.11
   203.5 2481.81   267.4 2478.75     295 2480.39   332.9 2480.11     356 2481.88
   433.3 2480.21   453.5 2477.62   473.6 2479.65   489.7 2477.75   509.9 2478.02
     522 2475.98   534.1 2475.43   558.3 2475.97   578.4 2478.48   598.6 2478.31
   606.6 2479.31   633.8  2480.3   639.3 2480.26   645.6 2478.73   656.9 2477.78
   688.7 2480.28   722.4 2480.73   798.4 2496.86   815.9 2502.19   830.7 2508.61
#Mann= 7 ,-1,0
       0     .12       0     120     .08       0     180     .06       0
     522    .045       0   558.3     .06       0  651.87     .12       0
  741.87     .06       0
#XS Ineff= 2 , 0
          354.93 2483.94  634.37         2482.37
Permanent Ineff=
       F       F
Bank Sta=522,558.3
XS Rating Curve= 0 ,0
Exp/Cntr(USF)=0,0
Exp/Cntr=0.3,0.1

Type RM Length L Ch R = 1 ,12964   ,339.9,333.8,319.5
XS GIS Cut Line= 2
2265413.78904786403100.3631095842266289.19315512402998.187947194
#Sta/Elev= 30
       0 2491.77    18.5 2490.67    30.6 2486.22    38.6 2484.97   307.9 2482.43
   336.7 2477.56   348.7 2476.63   354.62474.472   360.8  2473.6   376.5 2474.26
   397.1 2473.71   401.7 2474.49   413.2 2476.71   429.3 2477.21   473.3 2477.41
   485.7 2476.18   497.7 2476.99   521.9 2476.88     534 2478.57   558.1 2479.38
   590.4 2478.32   642.7 2481.09     691 2481.01   699.1  2481.9     724 2481.98
   779.6 2485.67   807.8 2488.97     836 2489.26   872.3  2487.8   881.3 2488.17
#Mann= 7 ,-1,0
       0     .06       0     290      .1       0     310     .12       0
   354.6    .045       0   401.7     .12       0     590      .1       0
     790     .06       0
#XS Ineff= 2 , 0
                          557.75         2481.93
Permanent Ineff=
       F       F
Bank Sta=354.6,401.7
XS Rating Curve= 0 ,0
Exp/Cntr=0.3,0.1

Type RM Length L Ch R = 1 ,12631   ,227.1,229,225
XS GIS Cut Line= 3
2265730.26701432403498.276490852  2265999.197875403196.549183748
 2266270.7524514403020.760230914
#Sta/Elev= 30
       0 2541.58    20.9  2535.5    44.6 2524.88    60.4 2514.96    81.8 2496.88
    92.8 2489.53   103.3 2487.92   119.4 2489.16   135.3 2488.12   147.1 2480.49
   152.3 2479.08   165.2 2478.38   177.2 2472.55     189 2471.72   197.6 2472.52
   210.4 2472.85   221.2  2474.3   255.4 2473.69   285.4 2475.56   301.5 2474.04
   344.4 2473.37   381.8    2477   443.5 2476.64   469.3 2477.92   562.6  2478.5
   572.2 2479.25   595.3 2485.37   606.9 2486.79   647.4 2488.07   727.7 2488.83
#Mann= 8 ,-1,0
       0      .1       0      60     .07       0     100     .06       0
   177.2    .045       0   197.6      .1       0     250     .12       0
  634.18      .1       0  654.18     .06       0
Bank Sta=177.2,197.6
XS Rating Curve= 0 ,0
Exp/Cntr(USF)=0,0
Exp/Cntr=0.3,0.1

Type RM Length L Ch R = 1 ,12402   ,185.9,185,183.6
XS GIS Cut Line= 2
 2265954.8708797403532.558628376     2266320.475      403075.935
#Sta/Elev= 30
       0 2487.37    19.7 2487.34    24.8 2486.55    27.7 2485.07    40.3 2476.19
      46 2474.07    76.1 2474.39    88.7 2472.87   104.5 2473.56   111.9 2472.07
     120 2471.21   137.1 2470.83  143.38 2471.17   173.4 2474.06     199 2473.28
   219.5 2473.99   232.5  2475.6   251.7  2475.3   265.7 2474.36   306.7 2475.99
   333.4 2475.23   386.1 2475.61   393.8 2476.68   409.1 2483.32   424.5 2485.19
   460.4 2485.98   482.1  2485.9   542.4 2487.42   578.2 2487.31     585 2488.02
#Mann= 8 ,-1,0
       0      .1       0      70     .06       0     100      .1       0
     120    .045       0  143.38      .1       0     220     .12       0
     480      .1       0     540     .06       0
#XS Ineff= 2 , 0
                          234.93          2477.9
Permanent Ineff=
       F       F
Bank Sta=120,143.38
XS Rating Curve= 0 ,0
Exp/Cntr=0.3,0.1

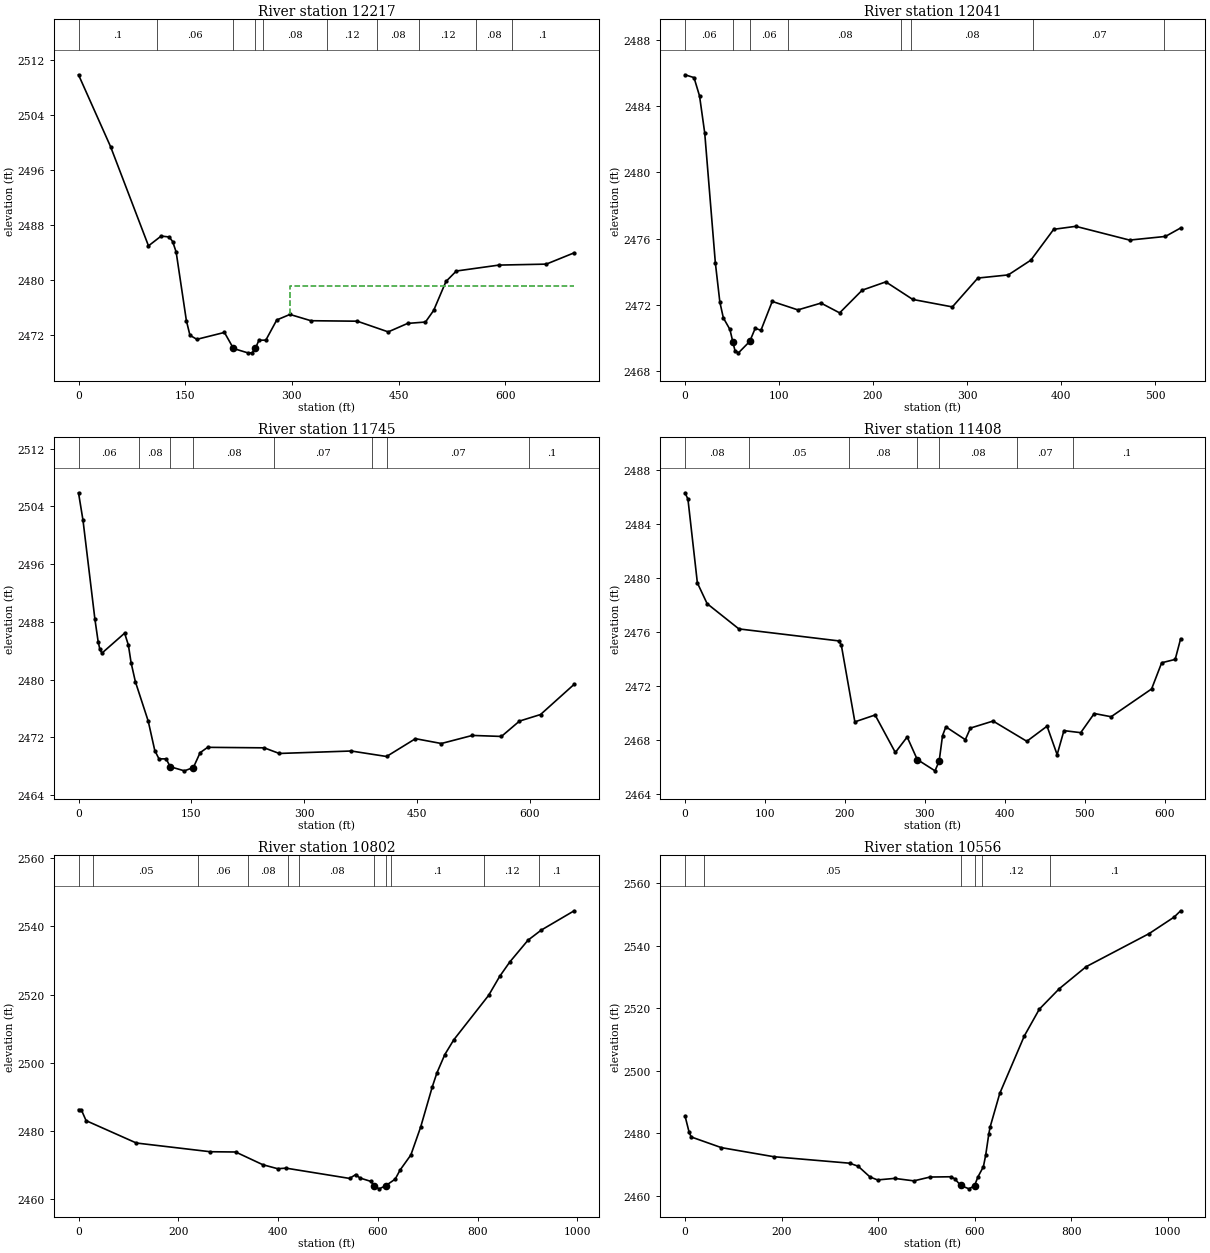
Type RM Length L Ch R = 1 ,12217   ,171.6,175.9,181.4
XS GIS Cut Line= 3
2266046.42475785403738.346478678 2266215.6544214403491.717201567
 2266478.0259928403192.613610177
#Sta/Elev= 30
       0 2509.79    45.1 2499.36    98.4 2484.97   116.2 2486.39   127.5 2486.26
   132.4 2485.59   137.3 2484.08   151.7 2474.11   156.7    2472   166.4 2471.41
   205.2 2472.41   217.9 2470.08     238 2469.45     244 2469.45   248.8 2470.11
   253.7 2471.28   263.4 2471.29   278.8 2474.22   297.3 2475.02   326.8 2474.11
     392 2474.04   435.5 2472.49   462.8 2473.72   487.9 2473.92   499.4  2475.6
   516.7  2479.8   531.3 2481.32   591.1 2482.18   657.8 2482.32     697 2483.96
#Mann= 10 ,-1,0
       0      .1       0     110     .06       0   217.9    .045       0
   248.8      .1       0     260     .08       0  349.11     .12       0
  419.11     .08       0  479.11     .12       0  559.11     .08       0
  609.11      .1       0
#XS Ineff= 2 , 0
                          297.35         2479.16
Permanent Ineff=
       F       F
Bank Sta=217.9,248.8
XS Rating Curve= 0 ,0
Exp/Cntr(USF)=0,0
Exp/Cntr=0.3,0.1

Type RM Length L Ch R = 1 ,12041   ,296.5,295.5,295.2
XS GIS Cut Line= 2
2266234.11140775403732.7221927292266586.74315511 403340.84519802
#Sta/Elev= 30
       0 2485.88     9.6 2485.71    15.5  2484.6      21 2482.37    32.3 2474.54
    37.1 2472.17    40.8 2471.22    47.8 2470.52    50.9 2469.77    53.2 2469.24
    56.9 2469.11    68.9  2469.8    74.7 2470.59    80.8 2470.47    92.8 2472.21
   120.1  2471.7   144.7 2472.11   164.5 2471.52   188.5 2472.89   213.6 2473.39
   242.3 2472.33   284.4 2471.88   311.5 2473.62   343.9 2473.81   367.9  2474.7
   392.2 2476.56   415.7 2476.74   472.9 2475.91     511 2476.13   527.2 2476.64
#Mann= 8 ,-1,0
       0     .06       0    50.9    .045       0    68.9     .06       0
     110     .08       0     230     .05       0     240     .08       0
     370     .07       0     510      .1       0
Bank Sta=50.9,68.9
XS Rating Curve= 0 ,0
Exp/Cntr=0.3,0.1

Type RM Length L Ch R = 1 ,11745   ,341,337.7,326.4
XS GIS Cut Line= 3
2266439.01831451403957.9480000522266716.78353066403592.170570181
     2266710.935      403392.496
#Sta/Elev= 30
       0  2505.9       6 2502.06    21.8 2488.37    26.1 2485.26    28.4 2484.19
    31.1 2483.66    61.3 2486.43    66.3 2484.78    69.9 2482.34    75.6  2479.7
    92.7 2474.23   101.4 2470.16     107    2469   116.5    2469121.94492467.908
   140.8 2467.34   152.7  2467.8   161.7 2469.86   171.7  2470.6   246.9 2470.53
   266.9 2469.75   362.6 2470.09   409.6 2469.33     448  2471.8   482.4 2471.13
   523.6 2472.25   562.3 2472.11   586.3 2474.24   614.3 2475.15     659 2479.34
#Mann= 8 ,-1,0
       0     .06       0      80     .08       0121.9449    .045       0
   152.7     .08       0     260     .07       0     390     .05       0
     410     .07       0  599.29      .1       0
Bank Sta=121.9449,152.7
XS Rating Curve= 0 ,0
Exp/Cntr=0.3,0.1

Type RM Length L Ch R = 1 ,11408   ,591.4,605.8,609.5
XS GIS Cut Line= 3
2266608.76552705404030.1228660052266787.91191714403954.060711551
2266922.02150526403550.731129379
#Sta/Elev= 30
       0 2486.29     3.7 2485.82    15.5 2479.61    27.7 2478.07    67.4  2476.2
   192.4 2475.31   195.5 2474.99   212.4 2469.31   237.7 2469.82     263 2467.04
   277.8 2468.19   290.4 2466.52   312.6 2465.68   317.8  2466.4     322 2468.29
   326.2 2468.94   350.5 2467.99   356.9 2468.85   385.2 2469.37   427.4 2467.87
   452.7 2468.99   465.3 2466.88   473.8 2468.66   494.8 2468.51   511.7 2469.93
   532.8 2469.69   583.4 2471.75     596 2473.69   612.9 2473.94   619.7 2475.47
#Mann= 7 ,-1,0
       0     .08       0      80     .05       0  204.62     .08       0
   290.4    .045       0   317.8     .08       0  414.62     .07       0
  484.62      .1       0
Bank Sta=290.4,317.8
XS Rating Curve= 0 ,0
Exp/Cntr(USF)=0,0
Exp/Cntr=0.3,0.1

Type RM Length L Ch R = 1 ,10802   ,246.4,245.9,243.6
XS GIS Cut Line= 5
2266658.26397096404082.5860646912267058.16017757403946.608551332
2267112.96519557403944.308162223 2267353.0351834403738.346478678
2267542.77151154  403674.4750429
#Sta/Elev= 30
       0 2486.34     5.8  2486.2    15.2 2483.08     116 2476.53     264 2473.98
     315  2473.9   369.6 2470.17   399.2 2469.01   416.1 2469.17   543.5 2466.16
   555.8  2467.3     564  2466.3   586.7 2465.26592.47642464.001   602.7 2463.11
615.46032463.985   634.9 2465.96   644.8 2468.64   666.3 2473.03     686 2481.23
   709.3 2493.01   718.6  2497.1   734.4 2502.44   752.3 2506.75   822.3  2519.8
   844.3 2525.32   864.4 2529.51   901.1 2535.93   927.7 2538.89   993.7 2544.55
#Mann= 11 ,-1,0
       0     .06       0      30     .05       0     240     .06       0
     340     .08       0     420      .1       0  442.38     .08       0
592.4764    .045       0615.4603     .08       0  627.24      .1       0
  813.55     .12       0  923.55      .1       0
Bank Sta=592.4764,615.4603
XS Rating Curve= 0 ,0
Exp/Cntr=0.3,0.1

Type RM Length L Ch R = 1 ,10556   ,195,198.1,202.7
XS GIS Cut Line= 3
2266847.71683983404308.4960749722267172.87944394404225.213392971
     2267668.632      403743.775
#Sta/Elev= 30
       0 2485.59     8.7 2480.25      13 2478.81    75.4  2475.4   183.9  2472.5
   340.8 2470.43   358.7 2469.46   383.3 2466.02   398.9 2465.08   434.2 2465.57
   474.1 2464.78   507.5    2466   550.2 2466.09   558.7 2465.46   571.1 2463.32
   588.3 2462.23   599.8 2463.23   606.7 2466.01   618.1 2469.29   622.8  2472.9
   629.4 2479.81   632.2 2482.06     652 2492.72   702.9  2511.1     734 2519.66
   775.2 2526.18   830.9 2533.23   961.5 2543.82  1013.2 2549.09  1026.7 2551.11
#Mann= 6 ,-1,0
       0     .07       0      40     .05       0   571.1    .045       0
   599.8      .1       0  615.66     .12       0  755.66      .1       0
Bank Sta=571.1,599.8
XS Rating Curve= 0 ,0
Exp/Cntr=0.3,0.1