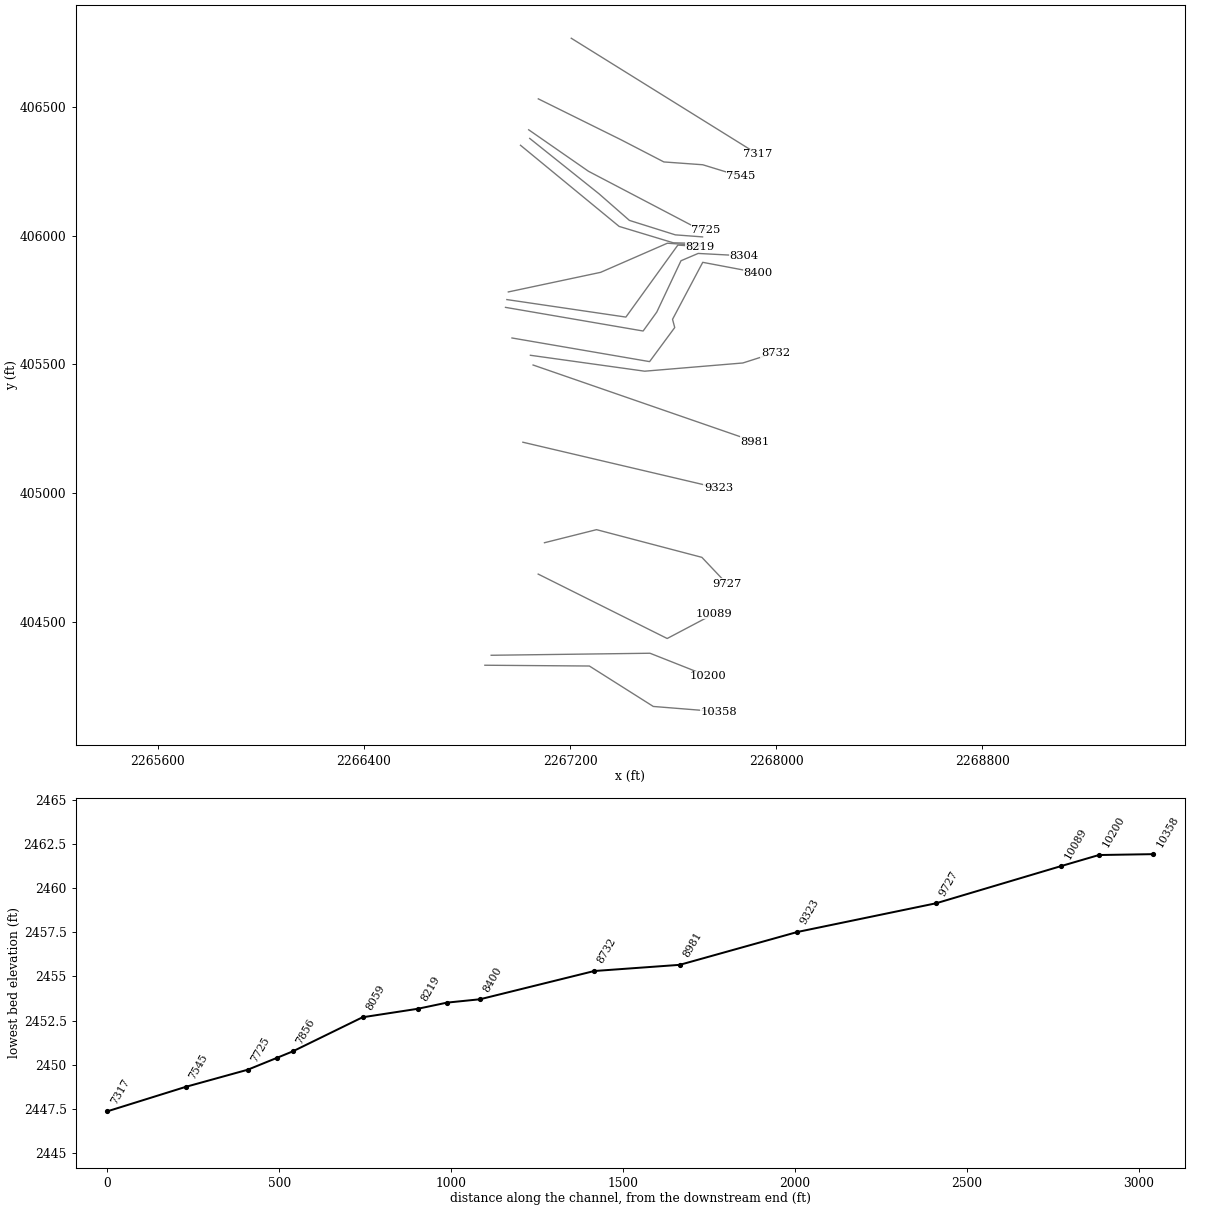
HEC-RAS study COCHRNCK.prj: COCHRNCK

--- COCHRNCK.g01 (geometry) --- (continued)

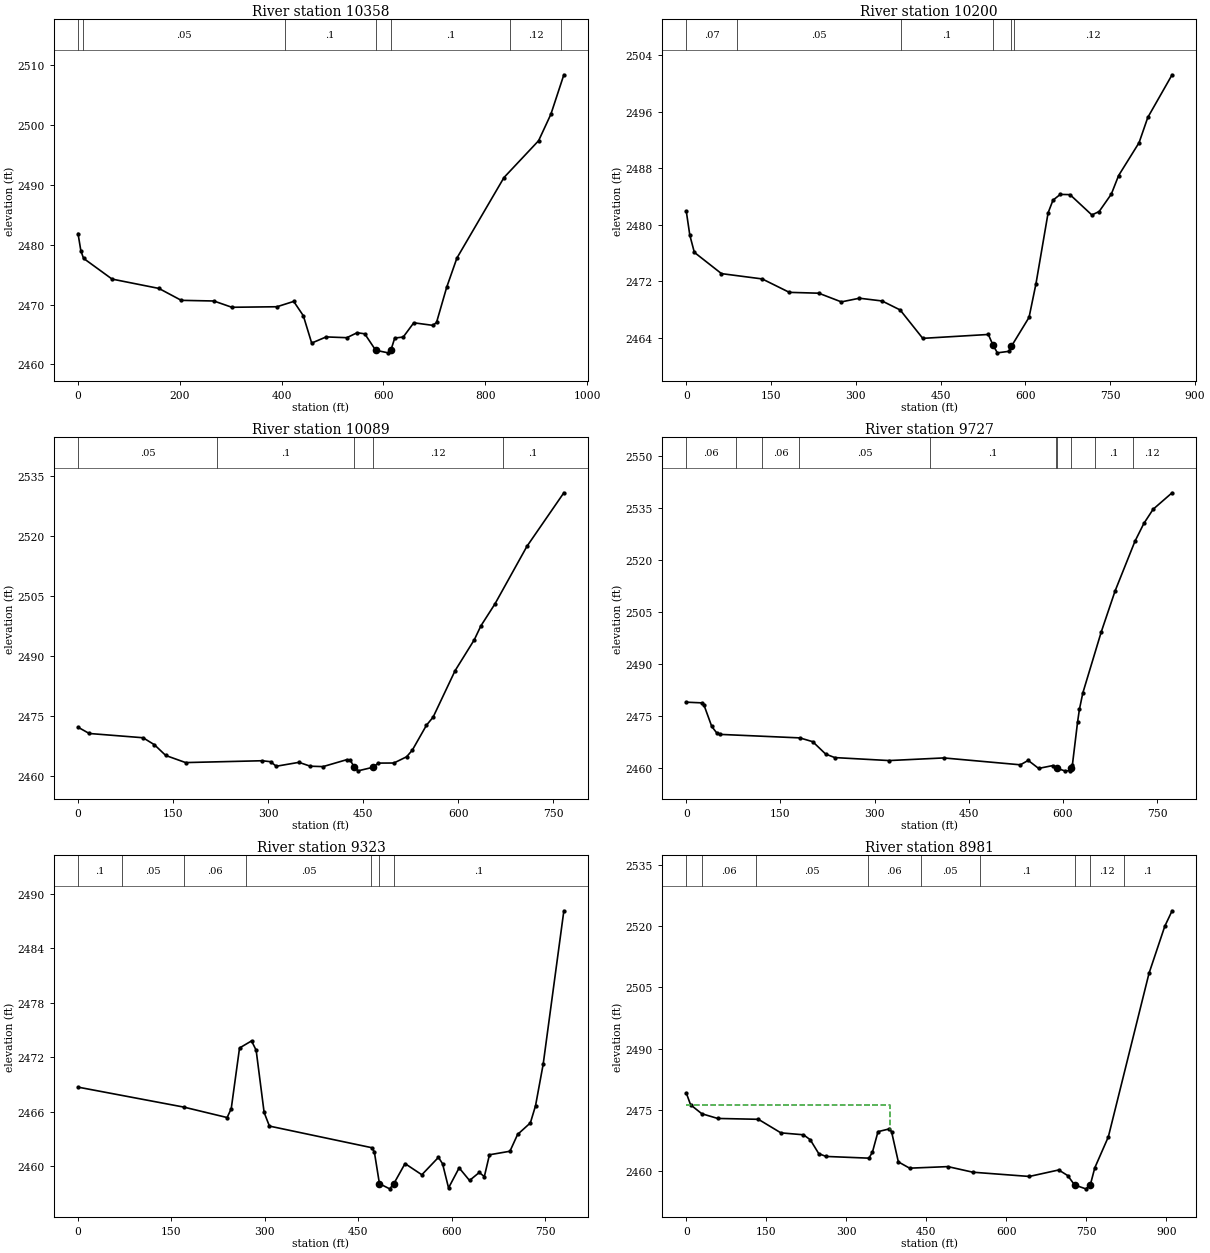
Type RM Length L Ch R = 1 ,10358   ,143.7,158.1,166.8
XS GIS Cut Line= 4
2266869.32396988 404331.991700432267275.08153823404328.940891646
2267523.23420381404171.9450418792267777.58022289404151.535806446
#Sta/Elev= 30
       0 2481.86     5.6 2478.97    10.9 2477.71    66.9 2474.25   158.9 2472.69
   202.9  2470.7   266.9 2470.59   302.3 2469.54   390.9 2469.63   423.8 2470.52
   442.7 2468.13   459.1 2463.56   487.5 2464.59   528.2 2464.46   548.4 2465.29
   563.3 2465.11   584.9 2462.36   609.3 2461.93   614.8 2462.39   622.3  2464.4
     639 2464.57   659.7 2466.95   697.1 2466.52   704.4    2467   724.4 2472.89
   744.5 2477.77     837 2491.22     905 2497.37   929.1 2501.79   954.6 2508.38
#Mann= 7 ,-1,0
       0     .07       0      10     .05       0  405.77      .1       0
   584.9    .045       0   614.8      .1       0  849.41     .12       0
  949.41      .1       0
Bank Sta=584.9,614.8
XS Rating Curve= 0 ,0
Exp/Cntr(USF)=0,0
Exp/Cntr=0.3,0.1

Type RM Length L Ch R = 1 ,10200   ,122.3,110.5,102.9
XS GIS Cut Line= 3
2266893.88493346404370.6619657392267510.45812624 404378.53311288
2267736.09767764404289.326778606
#Sta/Elev= 30
       0 2481.95     6.3 2478.53    14.3  2476.1    62.3 2473.09   134.3 2472.34
   182.3 2470.44   234.3 2470.32   274.3 2469.09   306.3 2469.61   346.3 2469.22
   378.3 2467.95   418.3 2463.93   534.3 2464.48   542.7 2462.94   550.3 2461.88
   570.3 2462.09   575.2 2462.82   606.3  2466.9   618.5 2471.64     640 2481.69
   648.6 2483.48   661.5  2484.3   678.7 2484.27   717.4 2481.39   730.3 2481.88
   751.8 2484.34   764.7 2486.97   800.9 2491.62   816.3 2495.19   859.3 2501.23
#Mann= 6 ,-1,0
       0     .07       0      90     .05       0     380      .1       0
   542.7    .045       0   575.2      .1       0     580     .12       0
Bank Sta=542.7,575.2
XS Rating Curve= 0 ,0
Exp/Cntr(USF)=0,0
Exp/Cntr=0.3,0.1

Type RM Length L Ch R = 1 ,10089   ,358,362.2,365
XS GIS Cut Line= 3
     2267076.363      404685.8182267577.18421301 404435.76582308
2267759.90776238404532.143330029
#Sta/Elev= 30
       0 2472.18    17.7 2470.61   102.6 2469.54   120.5 2467.79   138.4  2465.1
   169.7 2463.32   290.4 2463.78   303.8 2463.54   312.7  2462.4   348.5 2463.38
   366.4 2462.41   386.5 2462.31   423.8 2464.04   429.7 2463.85   435.7 2462.18
   435.7 2462.17   441.7 2461.25   465.5 2462.15   473.7 2463.19   498.3 2463.21
   518.4 2464.78   527.4 2466.45   549.7 2472.69   560.1 2474.69   594.8 2486.34
   625.2 2494.12   635.5 2497.57   657.8  2503.1   708.1 2517.49   766.4 2530.92
#Mann= 5 ,-1,0
       0     .05       0     220      .1       0   435.7    .045       0
   465.5     .12       0  669.77      .1       0
Bank Sta=435.7,465.5
XS Rating Curve= 0 ,0
Exp/Cntr=0.3,0.1

Type RM Length L Ch R = 1 ,9727    ,403.4,404.1,404.2
XS GIS Cut Line= 4
     2267100.751      404807.5942267302.88599519404858.333347825
 2267711.8621668404750.8381003022267809.90969637404647.302247529
#Sta/Elev= 30
       0 2478.99    24.6 2478.79    28.3 2478.12    40.6 2471.98    48.9 2470.02
      53 2469.69   180.9 2468.67   201.5 2467.57   222.1 2463.99   236.6 2462.98
   323.1 2462.12   410.2 2462.88   532.3 2460.89   544.7 2462.17   561.3 2459.85
   583.8 2460.67   590.1 2459.94   602.6 2459.15   610.9 2459.17   613.2 2459.94
   615.1 2460.85   623.3  2473.2   626.3 2476.94   631.7 2481.65   661.1 2499.31
   683.1 2511.12   714.7 2525.46   728.9 2530.62   743.7 2534.73   773.9 2539.49
#Mann= 10 ,-1,0
       0     .06       0      80     .05       0     120     .06       0
     180     .05       0  388.41      .1       0  588.41     .07       0
   590.1    .045       0   613.2     .07       0  651.27      .1       0
  711.27     .12       0
Bank Sta=590.1,613.2
XS Rating Curve= 0 ,0
Exp/Cntr=0.3,0.1

Type RM Length L Ch R = 1 ,9323    ,336.8,341.8,338.6
XS GIS Cut Line= 2
2267016.89519074405197.8107911132267776.54657809405019.338477218
#Sta/Elev= 30
       0 2468.72     170 2466.52   239.5 2465.37   246.1 2466.36   259.4 2473.03
   278.7 2473.81   286.1 2472.78   298.9 2465.93   307.4 2464.43   471.8 2462.05
   475.9  2461.6   484.1 2458.09   500.5 2457.52  507.032458.067   525.2  2460.3
   552.2 2459.07   578.9 2460.99   585.5 2460.28   595.1 2457.62   612.1 2459.83
   628.8 2458.44   644.4 2459.32   652.6 2458.87   660.8 2461.27   693.7 2461.66
     706 2463.51   726.5 2464.78   734.8 2466.67   747.1 2471.25   780.3 2488.14
#Mann= 7 ,-1,0
       0      .1       0      70     .05       0     170     .06       0
     270     .05       0     470      .1       0   484.1    .045       0
  507.03      .1       0
Bank Sta=484.1,507.03
XS Rating Curve= 0 ,0
Exp/Cntr(USF)=0,0
Exp/Cntr=0.3,0.1

Type RM Length L Ch R = 1 ,8981    ,238.7,248.6,255.5
XS GIS Cut Line= 2
2267056.55530772405497.547864878 2267917.1340619405199.756131345
#Sta/Elev= 30
       0 2479.15     8.1 2476.23    29.2 2474.04    58.9 2472.89   135.2 2472.68
   177.4 2469.36   219.7 2468.89   232.4 2467.68   248.4 2464.27     262 2463.59
   342.4 2463.17     349 2464.66   359.4 2469.66   380.3 2470.32   384.8 2469.66
   397.5 2462.26   418.6 2460.72   490.4  2461.1   537.2 2459.73     643 2458.69
   698.1 2460.28   714.9 2458.91   727.9 2456.61   748.8 2455.66   757.3 2456.62
   765.7  2460.8   791.1 2468.38   867.3 2508.39   896.9 2519.93   910.6 2523.72
#Mann= 9 ,-1,0
       0      .1       0      30     .06       0     130     .05       0
     340     .06       0     440     .05       0     550      .1       0
   727.9    .045       0   757.3     .12       0     820      .1       0
#XS Ineff= 2 , 0
          382.54 2476.29
Permanent Ineff=
       F       F
Bank Sta=727.9,757.3
XS Rating Curve= 0 ,0
Exp/Cntr(USF)=0,0
Exp/Cntr=0.3,0.1

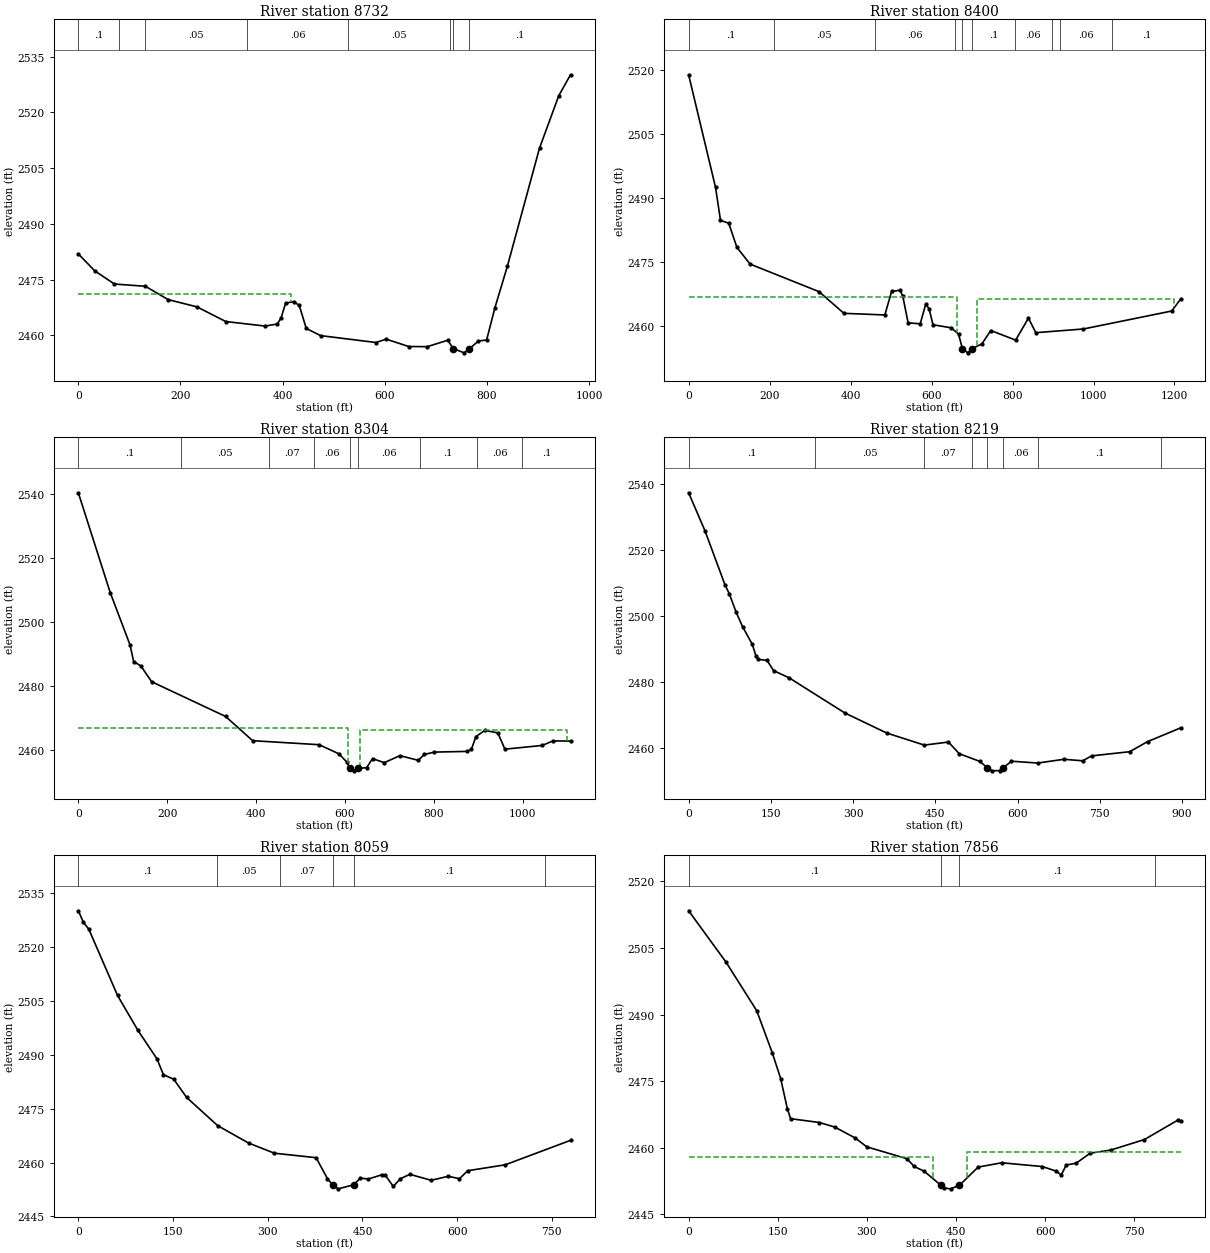
Type RM Length L Ch R = 1 ,8732    ,304.9,332,343.4
BEGIN DESCRIPTION:
structure xs 4
END DESCRIPTION:
XS GIS Cut Line= 4
2267046.15206523405535.3243435312267489.72440846405473.545465644
2267870.91717214405505.437638302 2267997.9930021 405545.99529008
#Sta/Elev= 30
       0 2481.93    32.1 2477.37    70.7 2473.82   131.3 2473.22   175.7 2469.64
   232.2 2467.68   288.8 2463.73   365.5 2462.52   389.7 2463.06   397.2 2464.77
   405.9  2468.7   421.5 2469.07   432.6 2468.08   446.3 2461.88   474.4 2459.94
   582.8 2458.09   602.8 2458.99     647 2457.01   683.1 2456.97   723.3 2458.69
   734.42456.457   755.4 2455.31765.49892456.359   783.5 2458.51   799.5 2458.75
   815.6 2467.38   840.1 2478.59   903.1  2510.4   940.9 2524.54   963.8 2530.12
#Mann= 8 ,-1,0
       0      .1       0      80     .06       0     130     .05       0
     330     .06       0  527.85     .05       0  727.85      .1       0
   734.4    .045       0765.4989      .1       0
#XS Ineff= 2 , 0
          416.34 2471.24
Permanent Ineff=
       F       F
Bank Sta=734.4,765.4989
XS Rating Curve= 0 ,0
Exp/Cntr(USF)=0,0
Exp/Cntr=0.5,0.3

Type RM Length L Ch R = 1 ,8400    ,99.6,96,92.9
BEGIN DESCRIPTION:
structure xs 3; 14.5 ft between structure and xs
END DESCRIPTION:
XS GIS Cut Line= 6
2266974.58578143405602.5014422462267508.86403074405510.718298309
2267606.44590966405643.0149398222267597.93589968405674.927477263
2267715.20548288405896.2184963232267930.25884221405855.551647261
#Sta/Elev= 30
       0 2518.82    66.5 2492.43    78.7 2484.75      99 2484.06   119.3 2478.39
   151.8 2474.49   322.2 2468.03   383.5 2462.96   484.6 2462.58   501.3 2468.08
   522.1 2468.38     529 2466.97   542.1 2460.73     572 2460.51   585.6 2465.11
   593.8 2464.05   603.6 2460.29   648.9 2459.56   666.7 2458.07   676.3 2454.65
   689.8 2453.71   699.12454.633   724.4 2455.82   746.3 2458.94   807.7 2456.69
   839.3 2461.83   857.5 2458.43   975.2  2459.3  1193.1  2463.5  1215.6 2466.36
#Mann= 10 ,-1,0
       0      .1       0     210     .05       0     460     .06       0
  658.91      .1       0   676.3    .045       0   699.1      .1       0
  806.26     .06       0  896.26      .1       0  916.26     .06       0
  1046.7      .1       0
#XS Ineff= 2 ,-1
       0     662  2466.9     713    1200  2466.3
Permanent Ineff=
       F       F
Bank Sta=676.3,699.1
XS Rating Curve= 0 ,0
Exp/Cntr=0.5,0.3

Type RM Length L Ch R = 1 ,8304    ,78.6,85.2,89.5
BEGIN DESCRIPTION:
structure xs 2; 12.2 ft between structure
END DESCRIPTION:
XS GIS Cut Line= 6
2266949.46835815405721.3215074882267483.74660746405629.538363551
2267536.77020292405703.1168853362267630.71318432  405902.3243829
 2267697.4530287405930.712596826 2267875.6354828405921.325069678
#Sta/Elev= 30
       0 2540.32    71.7 2509.19   116.4 2492.81   124.5 2487.65   140.7 2486.26
   165.1 2481.33   331.6 2470.49   392.4 2462.93   542.2 2461.68     587  2458.8
   604.3 2456.26  611.272454.306   619.7 2453.52   630.3 2454.27   649.1 2454.52
   662.3 2457.34   688.6 2456.07     724 2458.26   765.4  2456.8   778.9 2458.64
   801.5 2459.37   875.6 2459.59   884.8 2460.21     895 2464.21   915.1 2466.13
   944.3 2465.37   960.3 2460.28  1043.9 2461.44  1068.5 2462.86    1108 2462.82
#Mann= 9 ,-1,0
       0      .1       0     230     .05       0     430     .07       0
     530     .06       0  611.27    .045       0   630.3     .06       0
  768.44      .1       0  897.02     .06       0  999.55      .1       0
#XS Ineff= 2 ,-1
       0     607  2466.9     634    1100  2466.3
Permanent Ineff=
       F       F
Bank Sta=611.27,630.3
XS Rating Curve= 0 ,0
Exp/Cntr=0.5,0.3

Type RM Length L Ch R = 1 ,8219    ,170.8,160.4,148.7
BEGIN DESCRIPTION:
structure xs 1
END DESCRIPTION:
XS GIS Cut Line= 4
2266954.71932596405751.5504161352267416.82533255405683.593650459
2267618.55324778405963.1240655722267704.48346596405957.449428523
#Sta/Elev= 30
       0 2537.41    29.8 2525.91    66.2 2509.57    74.2 2506.82    86.4 2501.35
    98.5 2496.81   116.2 2491.49   122.8 2487.99   126.7 2486.95     143 2486.63
   155.1 2483.52   183.4 2481.34   284.5 2470.75   361.3 2464.63     430 2460.97
     474 2461.89   493.7 2458.36   530.8 2456.06   545.1 2454.12   553.7 2453.17
     568 2453.26   573.8 2454.06     589 2456.09   636.8 2455.53   684.7 2456.67
   718.9 2456.21   735.4 2457.71   804.5 2458.96   837.2 2462.01   897.9 2466.21
#Mann= 8 ,-1,0
       0      .1       0     230     .05       0     430     .07       0
  517.08      .1       0   545.1    .045       0   573.8     .06       0
  637.08      .1       0   861.8     .06       0
Bank Sta=545.1,573.8
XS Rating Curve= 0 ,0
Exp/Cntr(USF)=0,0
Exp/Cntr=0.3,0.1

Type RM Length L Ch R = 1 ,8059    ,221.5,202.6,176.8
BEGIN DESCRIPTION:
structure xs 4
END DESCRIPTION:
XS GIS Cut Line= 4
2266960.40530128 405781.247789962267318.69808147405857.309944414
2267577.90989731405970.4023582742267708.01621414405961.394997878
#Sta/Elev= 30
       0 2530.09     7.9 2526.93    16.6 2524.96    62.1 2506.51    94.2 2496.85
   124.6 2488.85   134.7 2484.48   151.1  2483.2   171.5 2478.13   220.6 2470.29
   269.7 2465.43   310.5 2462.61   376.6 2461.36   394.6 2455.49   402.8  2453.8
   411.5 2452.69     436 2453.81   446.4 2455.65   459.5 2455.44   481.4 2456.64
     486 2456.52   498.8 2453.35   510.1 2455.51     525 2456.73   558.7 2455.07
     586 2456.19   603.6 2455.51   616.6 2457.73   676.1 2459.38   779.5 2466.19
#Mann= 6 ,-1,0
       0      .1       0     220     .05       0     320     .07       0
   402.8    .045       0     436      .1       0  739.09     .06       0
Bank Sta=402.8,436
XS Rating Curve= 0 ,0
Exp/Cntr(USF)=0,0
Exp/Cntr=0.5,0.3

Type RM Length L Ch R = 1 ,7856    ,46.7,46.4,45.7
BEGIN DESCRIPTION:
structure xs 3; 13.4 ft between structure and xs
END DESCRIPTION:
XS GIS Cut Line= 4
2267007.65565563406350.6556766492267390.68469853406035.583399426
 2267600.7186742405972.0413523642267713.48971434405969.166039829
#Sta/Elev= 30
       0 2513.39    62.8 2501.85   114.6 2490.88   140.7 2481.43   154.9 2475.59
   166.2 2468.77   171.6 2466.56   220.2  2465.7   245.8 2464.68   280.4 2462.21
   299.8 2460.22   367.5 2457.54   379.4 2455.81   396.4 2454.72   424.8 2451.53
   430.5 2450.94   440.9 2450.76   455.7 2451.56   487.2 2455.66   526.8 2456.63
   595.3 2455.78   618.7 2454.74   627.1 2453.88   635.4 2456.13   652.1 2456.53
   675.6 2458.78   710.8 2459.51   766.9 2461.86     823 2466.22   828.2 2466.13
#Mann= 4 ,-1,0
       0      .1       0   424.8    .045       0   455.7      .1       0
   785.4     .06       0
#XS Ineff= 2 , 0
             411    2458     469          2459.1
Permanent Ineff=
       F       F
Bank Sta=424.8,455.7
XS Rating Curve= 0 ,0
Exp/Cntr(USF)=0,0
Exp/Cntr=0.5,0.3

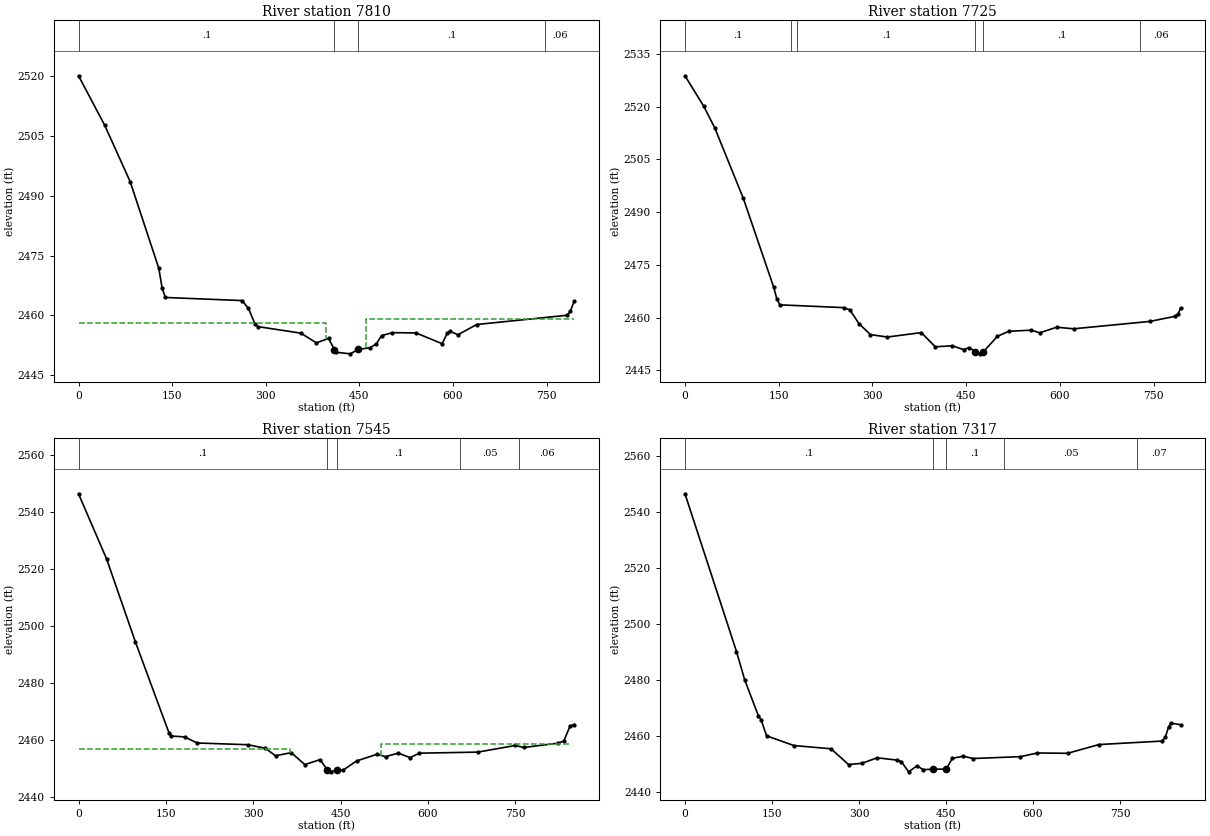
Type RM Length L Ch R = 1 ,7810    ,84.3,84.6,86.5
BEGIN DESCRIPTION:
structure xs 2; 16.4 ft between structure and xs
END DESCRIPTION:
XS GIS Cut Line= 5
 2267043.4874048 406377.220594142267312.12284711406162.547024737
2267430.56975988406058.9056671742267608.82529856406002.846524918
2267714.46297878405994.920294885
#Sta/Elev= 30
       0 2520.08    41.8 2507.73    82.8 2493.53   128.6 2471.85     134 2466.85
   139.1 2464.52     262 2463.74   272.3 2461.77   282.5 2457.99   287.6 2457.21
   356.2 2455.57   381.1 2453.15   400.6 2454.25   410.1 2451.43     413 2450.78
   435.6 2450.39   448.1  2451.5   466.8 2451.91   476.8 2452.84   485.7 2454.96
   502.9  2455.7   540.7 2455.63   582.6 2452.93     591 2455.64   595.2 2456.07
   607.8 2455.16   637.9 2457.74   782.4 2460.05   787.8 2461.01   794.1 2463.53
#Mann= 4 ,-1,0
       0      .1       0   410.1    .045       0   448.1      .1       0
  748.13     .06       0
#XS Ineff= 2 , 0
             396    2458     460          2459.1
Permanent Ineff=
       F       F
Bank Sta=410.1,448.1
XS Rating Curve= 0 ,0
Exp/Cntr(USF)=0,0
Exp/Cntr=0.5,0.3

Type RM Length L Ch R = 1 ,7725    ,178.4,180.1,177.3
BEGIN DESCRIPTION:
structure xs 1
END DESCRIPTION:
XS GIS Cut Line= 4
 2267039.4699092406410.7621998522267271.65964385406249.630530547
2267666.98268345406042.4612414412267728.03257057406022.444885006
#Sta/Elev= 30
       0 2528.78    30.1 2520.09    47.6    2514    93.4 2493.91   142.1  2468.6
   146.9  2465.4   151.8 2463.65     254 2462.86   263.8 2462.23   278.4 2458.32
   296.8 2455.19   323.8  2454.5   378.2 2455.76   400.6 2451.72   427.7 2452.01
   445.8 2450.93   454.8  2451.5   464.6 2450.38   472.9 2449.72   477.4 2450.27
     500 2454.71     518 2456.12   554.2 2456.46   567.7 2455.69   594.8 2457.29
   621.9 2456.84   743.6 2458.93   784.8  2460.4   789.1 2460.98   793.2 2462.76
#Mann= 6 ,-1,0
       0      .1       0     170     .06       0     180      .1       0
   464.6    .045       0   477.4      .1       0  728.94     .06       0
Bank Sta=464.6,477.4
XS Rating Curve= 0 ,0
Exp/Cntr(USF)=0,0
Exp/Cntr=0.3,0.1

Type RM Length L Ch R = 1 ,7545    ,229.1,228.7,227
XS GIS Cut Line= 5
2267076.81583168406530.8421287122267397.58868877406372.213323248
2267564.22564451406285.9602997122267715.26665109406274.999592806
 2267862.8688309406229.718930978
#Sta/Elev= 30
       0 2546.31    48.4 2523.37    97.5 2494.44   155.5 2462.35     159 2461.32
   182.2 2461.01   203.8 2458.87   290.4 2458.27   320.6 2457.05   338.4 2454.38
   365.3 2455.49   388.7 2451.29   414.8 2453.04   427.3 2449.46   432.8 2448.75
443.4198 2449.45     454 2449.29   477.6 2452.57   512.4 2454.88   527.4 2454.09
   549.4 2455.31   569.5 2453.72   585.5  2455.3   685.8 2455.67   750.3    2458
   764.8  2457.3     824 2458.81   833.6  2459.6   844.3 2464.85   851.3 2465.35
#Mann= 5 ,-1,0
       0      .1       0   427.3    .045       0443.4198      .1       0
  655.49     .05       0  756.93     .06       0
#XS Ineff= 2 ,-1
       0   363.2 2456.88  520.08   844.5 2458.48
Permanent Ineff=
       F       F
Bank Sta=427.3,443.4198
XS Rating Curve= 0 ,0
Exp/Cntr=0.3,0.1

Type RM Length L Ch R = 1 ,7317    ,270.4,276.2,276.6
XS GIS Cut Line= 2
2267204.79524556 406766.114412572267930.25264047406314.835309772
#Sta/Elev= 30
       0 2546.42    88.8 2490.22   102.9 2480.15   126.5 2467.35   131.2 2465.95
   140.6  2460.2   187.7 2456.72   251.7 2455.58   281.9 2449.97   304.7 2450.38
   331.3 2452.37   365.3 2451.54   372.8 2451.02   385.6 2447.36   399.7 2449.49
   410.7 2448.16   427.1 2448.27   450.4 2448.36   460.9  2452.2   479.8 2452.91
   496.8 2452.11   578.2 2452.77   607.6 2454.08   659.5 2453.96   713.6 2457.08
   822.1 2458.32   827.9 2459.67   833.7  2463.4   837.8 2464.74   854.4 2464.12
#Mann= 5 ,-1,0
       0      .1       0   427.1    .045       0   450.4      .1       0
     550     .05       0     780     .07       0
Bank Sta=427.1,450.4
XS Rating Curve= 0 ,0
Exp/Cntr(USF)=0,0
Exp/Cntr=0.3,0.1