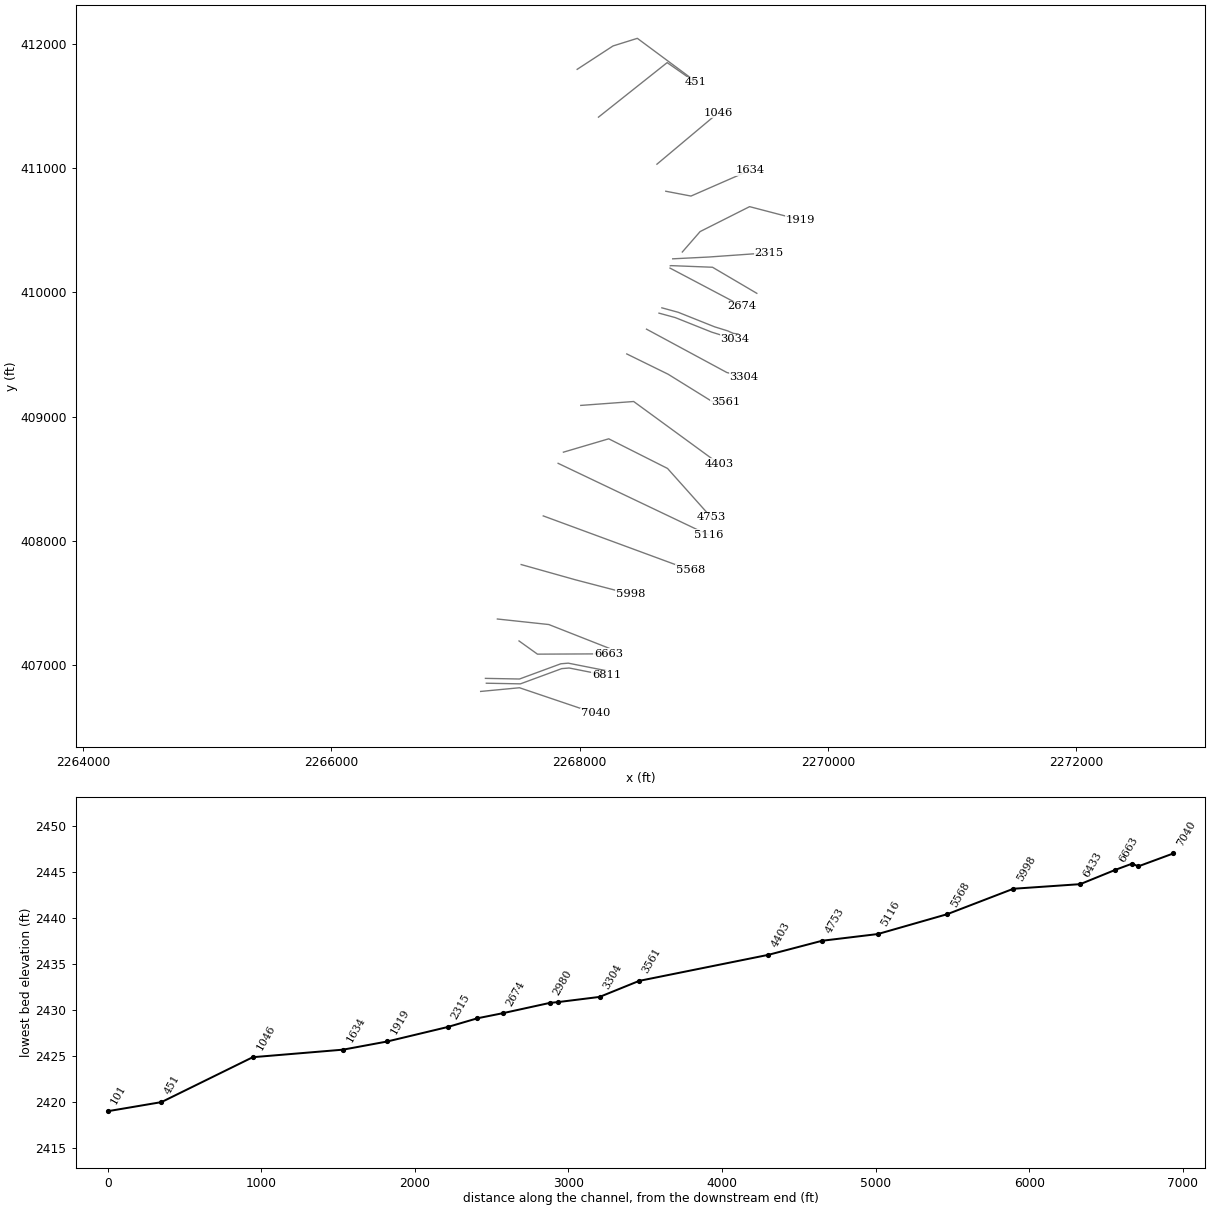
HEC-RAS study COCHRNCK.prj: COCHRNCK

--- COCHRNCK.g01 (geometry) --- (continued)

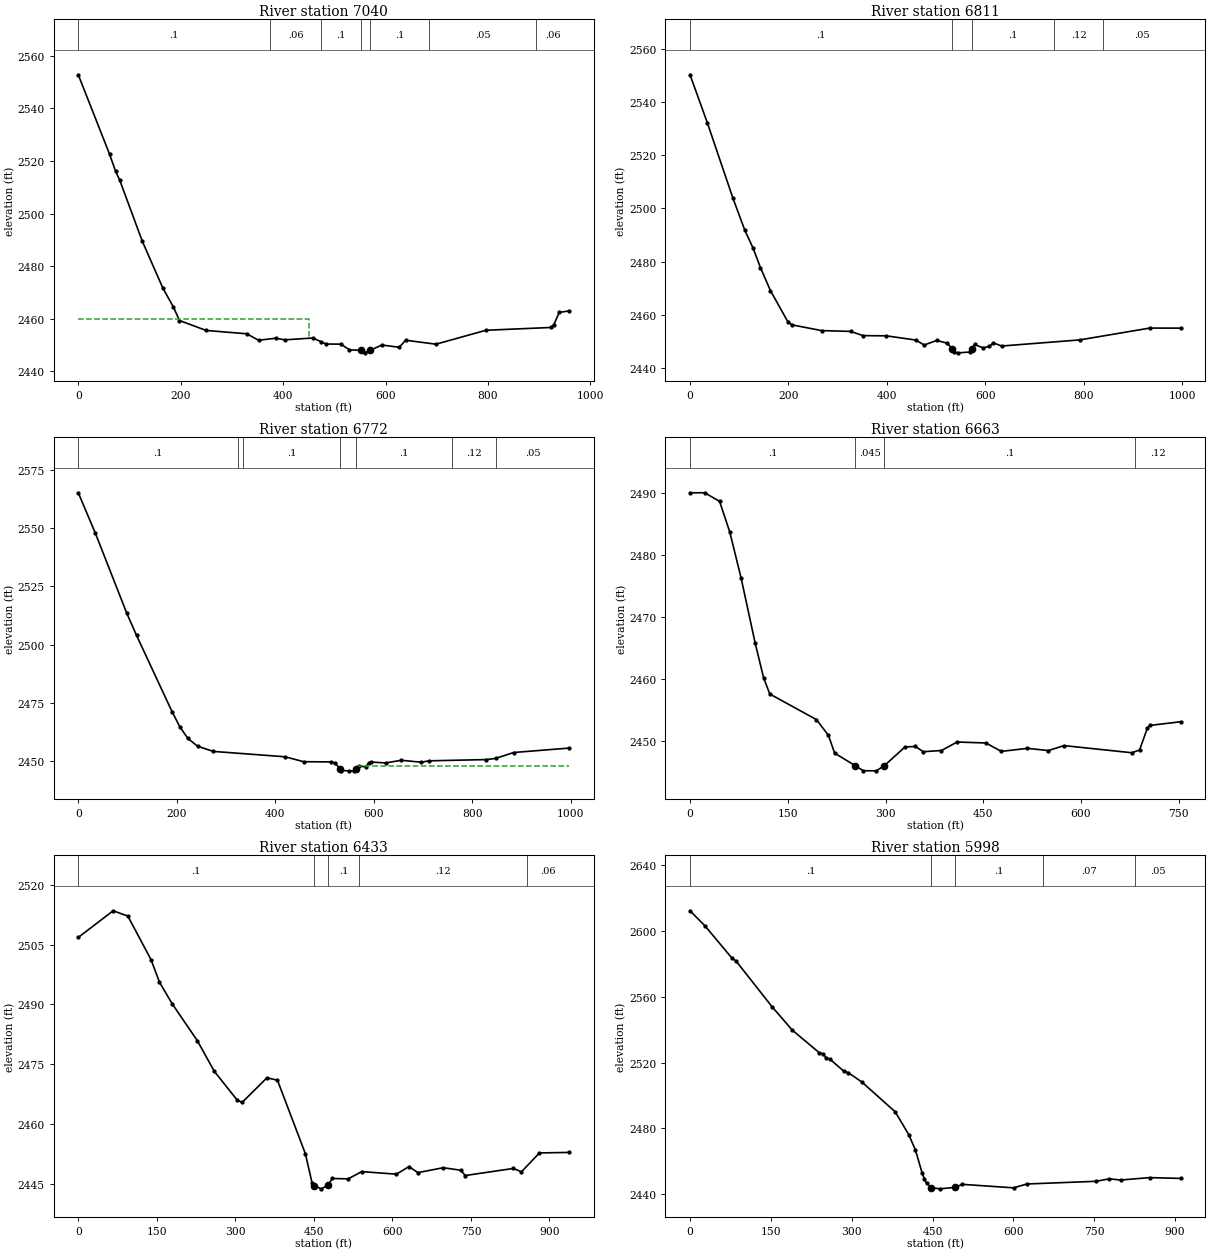
Type RM Length L Ch R = 1 ,7040    ,211.1,229.4,241.1
BEGIN DESCRIPTION:
structure xs 4
END DESCRIPTION:
XS GIS Cut Line= 3
2267203.48609347406786.2754370142267516.08721557  406815.9292984
2268126.46252909406609.587846258
#Sta/Elev= 30
       0 2552.82      61 2522.66      73 2516.06    81.1 2512.65   125.2 2489.41
   165.4 2471.57   185.5 2464.58   197.6 2459.35   249.8 2455.56   328.9  2454.3
   352.1 2451.82   385.9 2452.62   402.8 2451.99   457.7 2452.69     474 2451.28
   483.5  2450.4   512.5 2450.36   529.4 2448.22   552.2 2447.98   559.2 2447.05
   570.32448.053   592.8 2450.02   626.6 2449.16   639.2 2451.85   698.3 2450.34
   795.9 2455.64   922.1 2456.69   928.5 2457.78     939 2462.42   958.3    2463
#Mann= 7 ,-1,0
       0      .1       0     374     .06       0     474      .1       0
   552.2    .045       0   570.3      .1       0     684     .05       0
     894     .06       0
#XS Ineff= 2 , 0
             450    2460
Permanent Ineff=
       F       F
Bank Sta=552.2,570.3
XS Rating Curve= 0 ,0
Exp/Cntr(USF)=0,0
Exp/Cntr=0.5,0.3

Type RM Length L Ch R = 1 ,6811    ,39.7,39.2,39.2
BEGIN DESCRIPTION:
structure xs 3; 14.8 ft between structure and xs
END DESCRIPTION:
XS GIS Cut Line= 5
2267249.05923495406852.4073164152267523.38740317406847.300143071
2267856.08326675406969.872303338 2267915.9101545406974.979476683
2268217.96297802406915.152588933
#Sta/Elev= 30
       0 2550.29    35.1 2532.25    87.1 2503.88   111.1 2491.88     128 2485.07
   143.1  2477.7   163.3 2469.08   198.7 2457.33   207.2 2456.17   267.2 2454.01
   326.4 2453.71   351.2 2452.12   398.8 2452.04   458.5 2450.45   475.6 2448.58
   501.1 2450.31   522.5 2449.27   531.9 2447.27   535.2 2446.12   543.8 2445.64
   569.1 2445.95   572.4 2447.18   577.9 2448.81   594.9 2447.52   607.7 2448.06
   616.2 2449.37     633 2448.21   791.2  2450.5   933.9 2454.96   996.9 2454.94
#Mann= 5 ,-1,0
       0      .1       0   531.9    .045       0   572.4      .1       0
  738.98     .12       0  838.98     .05       0
#XS Ineff= 2 , 0
             516  2447.8     587          2448.1
Permanent Ineff=
       F       F
Bank Sta=531.9,572.4
XS Rating Curve= 0 ,0
Exp/Cntr(USF)=0,0
Exp/Cntr=0.5,0.3

Type RM Length L Ch R = 1 ,6772    ,116.2,108.7,99.6
BEGIN DESCRIPTION:
structure xs 2; 12.2 ft between structure and xs
END DESCRIPTION:
XS GIS Cut Line= 5
2267241.76327303406891.4407126912267516.09144125406886.333539347
2267848.78730483407008.9056996142267908.61419258407014.012872958
 2268210.6670161406954.185985209
#Sta/Elev= 30
       0 2565.18    34.4 2548.01    98.4 2513.59   118.4 2503.99   190.4 2471.34
   206.4  2464.8   222.5 2459.85   242.5 2456.47   274.5 2454.27     420 2451.97
   457.8 2449.86   513.2 2449.77   521.7 2449.26  531.562446.807   534.5 2446.05
   550.8 2445.94   560.1 2445.94   564.3 2446.86   569.5 2448.14   583.4 2447.62
   589.9 2449.36   594.2 2449.71     624 2449.34   656.4 2450.47   696.1 2449.63
     713 2450.24   828.9 2450.77   847.6 2451.28   884.3  2453.8   996.9  2455.7
#Mann= 7 ,-1,0
       0      .1       0  324.38     .06       0  334.38      .1       0
  531.56    .045       0   564.3      .1       0  758.98     .12       0
  848.98     .05       0
#XS Ineff= 2 , 0
             527  2447.8     567          2448.1
Permanent Ineff=
       F       F
Bank Sta=531.56,564.3
XS Rating Curve= 0 ,0
Exp/Cntr(USF)=0,0
Exp/Cntr=0.5,0.3

Type RM Length L Ch R = 1 ,6663    ,236.8,229.7,218.8
BEGIN DESCRIPTION:
structure xs 1
END DESCRIPTION:
XS GIS Cut Line= 3
 2267512.3804829407192.7804535092267660.64978983407086.520783544
 2268231.4866215407088.991938659
#Sta/Elev= 30
       0    2490    22.5    2490    45.4 2488.62    61.1 2483.65    78.5 2476.24
    99.9 2465.85   112.9 2460.25   122.4 2457.63   193.9 2453.52   212.5 2450.97
   221.9 2448.12   253.9 2446.08   265.9 2445.29   285.9 2445.27   297.9 2446.07
   329.9 2449.11   345.9 2449.19   357.9 2448.35   385.9 2448.54   409.9 2449.91
   453.9 2449.75   477.9  2448.4   517.9 2448.89   549.9 2448.53   573.9 2449.33
   677.9 2448.18   689.9 2448.62   701.9 2452.14   705.9 2452.58   753.3 2453.17
#Mann= 4 ,-1,0
       0      .1       0   253.9    .045       0   297.9      .1       0
  682.41     .12       0
Bank Sta=253.9,297.9
XS Rating Curve= 0 ,0
Exp/Cntr(USF)=0,0
Exp/Cntr=0.3,0.1

Type RM Length L Ch R = 1 ,6433    ,427.7,435.2,431.9
XS GIS Cut Line= 3
2267337.96778878407369.476415841 2267752.0825291407324.987252187
2268236.89378878407134.232415841
#Sta/Elev= 30
       0  2506.8    66.6 2513.49    94.7 2512.15     139 2501.22   155.1 2495.57
   179.2 2490.18   227.5 2480.88   259.7 2473.22   303.9 2465.92   313.2 2465.42
   360.3 2471.57   380.4 2470.98   433.8 2452.51   446.7 2445.09   450.4 2444.52
   463.9 2443.71   476.8 2444.57   485.4 2446.31   515.5 2446.21   541.3 2448.03
   607.7 2447.39   631.5 2449.29   648.7 2447.78   697.1 2449.01   730.4 2448.38
     739 2447.05   831.1 2448.83   846.4 2447.97   880.8 2452.72   937.5 2452.85
#Mann= 5 ,-1,0
       0      .1       0   450.4    .045       0   476.8      .1       0
   536.5     .12       0   856.5     .06       0
Bank Sta=450.4,476.8
XS Rating Curve= 0 ,0
Exp/Cntr=0.3,0.1

Type RM Length L Ch R = 1 ,5998    ,429.4,430.2,420.7
XS GIS Cut Line= 3
2267529.62573267407807.9170165012267968.29473267407684.707016501
2268408.48873267407569.791016501
#Sta/Elev= 30
       0 2612.39    27.6 2603.27    77.4 2583.73    85.4 2581.81   152.2    2554
   189.6 2539.81   239.5 2526.09   247.6 2525.27   251.9 2523.06   260.2 2521.94
   285.2  2514.8   293.5  2513.9   318.9 2508.17   380.6 2490.09   405.7 2476.25
   418.1 2466.88   430.6 2452.85   434.7 2449.21   438.9  2446.6   447.2 2443.99
   463.8 2443.21   491.2 2444.11   505.1 2445.95   600.2 2443.82     625 2446.16
   753.2  2447.8     778 2449.31   798.6 2448.56   852.4 2450.04   910.6 2449.55
#Mann= 5 ,-1,0
       0      .1       0   447.2    .045       0   491.2      .1       0
  655.64     .07       0  825.64     .05       0
Bank Sta=447.2,491.2
XS Rating Curve= 0 ,0
Exp/Cntr=0.3,0.1

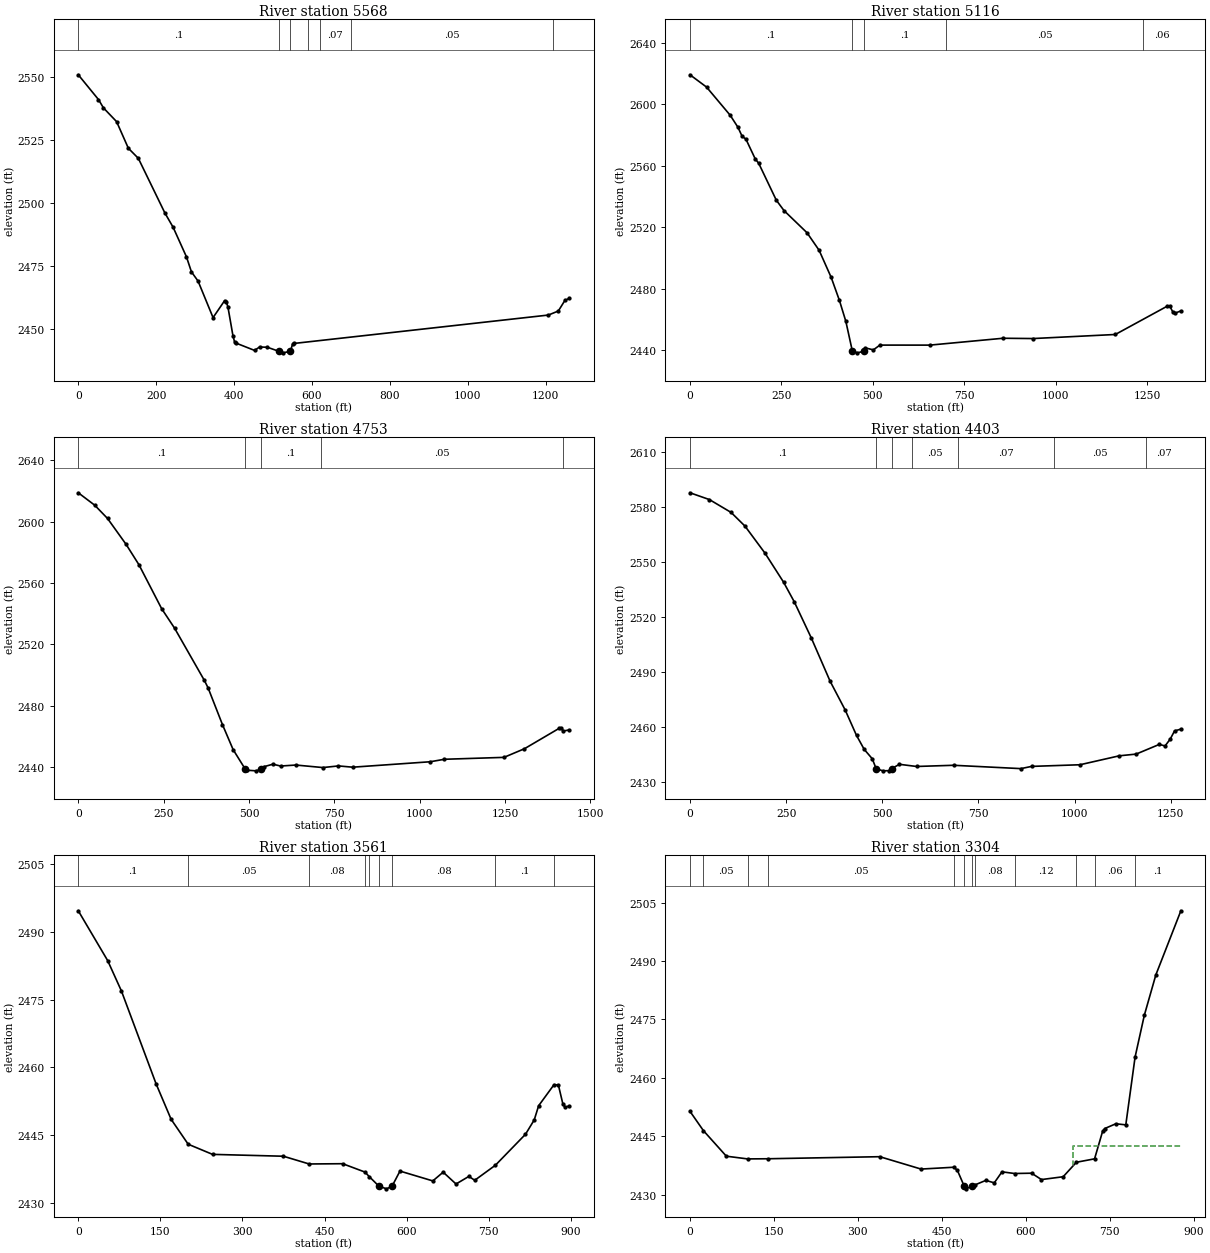
Type RM Length L Ch R = 1 ,5568    ,451.6,452.3,447.3
XS GIS Cut Line= 2
     2267707.456      408199.598 2268890.3590462407763.843508257
#Sta/Elev= 30
       0 2550.92    51.9 2541.08    64.7 2537.75    98.4 2532.31   128.6 2521.73
   154.2 2517.73   222.4 2496.02   243.7  2490.3   277.8 2478.59   290.6 2472.62
   307.6 2468.96   346.1 2454.45   375.9 2461.21   380.2 2460.72   384.4  2458.6
   397.2 2447.24   401.2  2444.9   404.3 2444.37   452.6 2441.42   465.4 2442.76
   485.3 2442.68   516.2 2441.01   525.1 2440.45   544.5 2441.04   550.7 2444.06
   553.8 2444.18  1207.1 2455.46  1232.7 2457.06  1249.8 2461.32  1260.6 2462.06
#Mann= 7 ,-1,0
       0      .1       0   516.2    .045       0   544.5      .1       0
     590     .05       0     620     .07       0     700     .05       0
    1220     .06       0
Bank Sta=516.2,544.5
XS Rating Curve= 0 ,0
Exp/Cntr=0.3,0.1

Type RM Length L Ch R = 1 ,5116    ,363.9,363,361.3
XS GIS Cut Line= 2
2267827.23994059408622.9603465362269039.40544884408045.400135318
#Sta/Elev= 30
       0 2619.07    45.3 2611.08   110.1 2592.73   131.1 2584.98   142.8 2578.99
   152.9 2577.29   178.3 2564.48   188.1 2561.48   236.1 2537.55   257.1 2530.81
   320.1 2516.38   353.2 2504.98   386.2 2487.37   408.7 2472.42   426.4 2458.71
   444.1 2439.46   458.2 2438.29   475.1 2439.32   479.6  2441.5   501.7 2440.22
   519.4 2443.32   656.2 2443.31   856.2 2447.77   938.3 2447.58  1163.4 2450.22
  1304.5 2468.51  1312.6 2468.49  1321.4 2464.58  1325.5    2464  1342.7 2465.53
#Mann= 5 ,-1,0
       0      .1       0   444.1    .045       0   475.1      .1       0
     700     .05       0    1240     .06       0
Bank Sta=444.1,475.1
XS Rating Curve= 0 ,0
Exp/Cntr=0.3,0.1

Type RM Length L Ch R = 1 ,4753    ,352.4,350.2,328.9
XS GIS Cut Line= 4
2267869.90717905408712.9114723172268234.60366328408820.483816589
2268708.18434965 408581.725686622269059.37175716408188.573223929
#Sta/Elev= 30
       0 2618.79   48.24 2610.68   85.78 2602.03  139.99 2585.19  177.52 2571.95
  244.25 2543.23  282.22 2530.48  369.36 2496.48  380.23 2491.62  422.31 2467.69
  453.66 2451.34   488.1 2439.02  493.98 2437.97  520.85 2437.56  536.462438.755
  543.26 2440.23  570.13 2441.89  592.53 2440.69  637.33 2441.34  716.33  2439.7
  762.09 2440.76  803.78 2439.94 1030.67 2443.48 1072.45  2445.1 1246.82 2446.34
 1306.87 2451.98 1408.94 2465.33 1414.94 2465.33 1420.95 2463.56 1437.76 2464.19
#Mann= 5 ,-1,0
       0      .1       0   488.1    .045       0  536.46      .1       0
  710.23     .05       0 1420.59     .06       0
Bank Sta=488.1,536.46
XS Rating Curve= 0 ,0
Exp/Cntr(USF)=0,0
Exp/Cntr=0.3,0.1

Type RM Length L Ch R = 1 ,4403    ,475.8,841.2,392.1
XS GIS Cut Line= 3
2268009.60724632409089.3830951292268435.44910805 409120.84722411
 2269121.3966014408619.907841037
#Sta/Elev= 30
       0 2587.67    50.7 2583.95   106.9 2576.96     143  2569.5   195.1 2554.74
   243.2 2538.98   271.3 2528.16   315.4 2508.53   364.5 2484.85   403.7 2469.16
     433 2455.36     453 2447.74   473.9 2442.64  484.172437.167   501.7 2436.03
   517.1 2436.13   524.32437.256   544.7 2439.59   589.2 2438.41   685.5 2439.06
   860.5 2437.24   888.2 2438.45  1014.1 2439.35  1116.4 2444.23  1160.1 2445.16
  1220.4 2450.45  1235.3  2449.6  1248.8 2453.37    1260 2457.82  1276.4 2458.77
#Mann= 7 ,-1,0
       0      .1       0  484.17    .045       0   524.3      .1       0
     577     .05       0     697     .07       0     947     .05       0
    1187     .07       0
Bank Sta=484.17,524.3
XS Rating Curve= 0 ,0
Exp/Cntr=0.3,0.1

Type RM Length L Ch R = 1 ,3561    ,252.7,257.3,256.6
XS GIS Cut Line= 4
2268379.94756436409503.9054521482268713.36186902409340.214248854
2269067.97262809409120.2814435772269175.86717492409113.351498349
#Sta/Elev= 30
       0  2494.6    53.7  2483.6    78.8  2476.9   142.3 2456.34   169.6 2448.56
   200.8 2443.05   245.3 2440.81   374.7  2440.4   421.8 2438.69     483 2438.75
   523.8  2436.9   531.9 2435.86   548.9 2433.83     563  2433.2   573.2 2433.77
   587.7 2437.12   647.7 2434.95   666.6 2436.88   690.1 2434.27   713.6 2435.95
   724.3 2435.09   762.1 2438.42     817 2445.25     833 2448.43     841 2451.55
   869.1  2456.2   877.1 2456.12   885.1 2452.04   889.1  2451.2   896.8 2451.52
#Mann= 9 ,-1,0
       0      .1       0   200.8     .05       0   421.8     .08       0
   523.8     .07       0   531.9     .08       0   548.9    .045       0
   573.2     .08       0   762.1      .1       0   869.1     .06       0
Bank Sta=548.9,573.2
XS Rating Curve= 0 ,0
Exp/Cntr=0.3,0.1

Type RM Length L Ch R = 1 ,3304    ,265.4,269.5,272.6
BEGIN DESCRIPTION:
structure xs 4
END DESCRIPTION:
XS GIS Cut Line= 3
 2268538.9546861409703.3641543322269185.70060959409354.409964377
2269323.44568457409318.989802239
#Sta/Elev= 30
       0 2451.38    24.1  2446.4      65 2439.85   102.9 2439.15   139.4 2439.19
   339.1 2439.72   412.9 2436.54   471.4 2437.01   477.8 2436.21   489.6 2432.28
   493.2 2431.46   504.4 2432.17     510 2432.52   528.6 2433.63   543.7    2433
   557.5 2435.83     580  2435.4   610.4 2435.48     628 2433.84   666.8 2434.57
   690.4 2438.29   722.9 2439.17   737.4 2446.31   741.2 2446.96   760.9 2448.18
   778.7  2447.9   795.3 2465.33   811.8 2476.06   832.4 2486.44   877.1 2502.91
#Mann= 12 ,-1,0
       0      .1       0    24.1     .05       0   102.9      .1       0
   139.4     .05       0   471.4      .1       0   489.6    .045       0
   504.4      .1       0     510     .08       0     580     .12       0
   690.4      .1       0   722.9     .06       0   795.3      .1       0
#XS Ineff= 2 , 0
                          684.39         2442.37
Permanent Ineff=
       F       F
Bank Sta=489.6,504.4
XS Rating Curve= 0 ,0
Exp/Cntr(USF)=0,0
Exp/Cntr=0.5,0.3

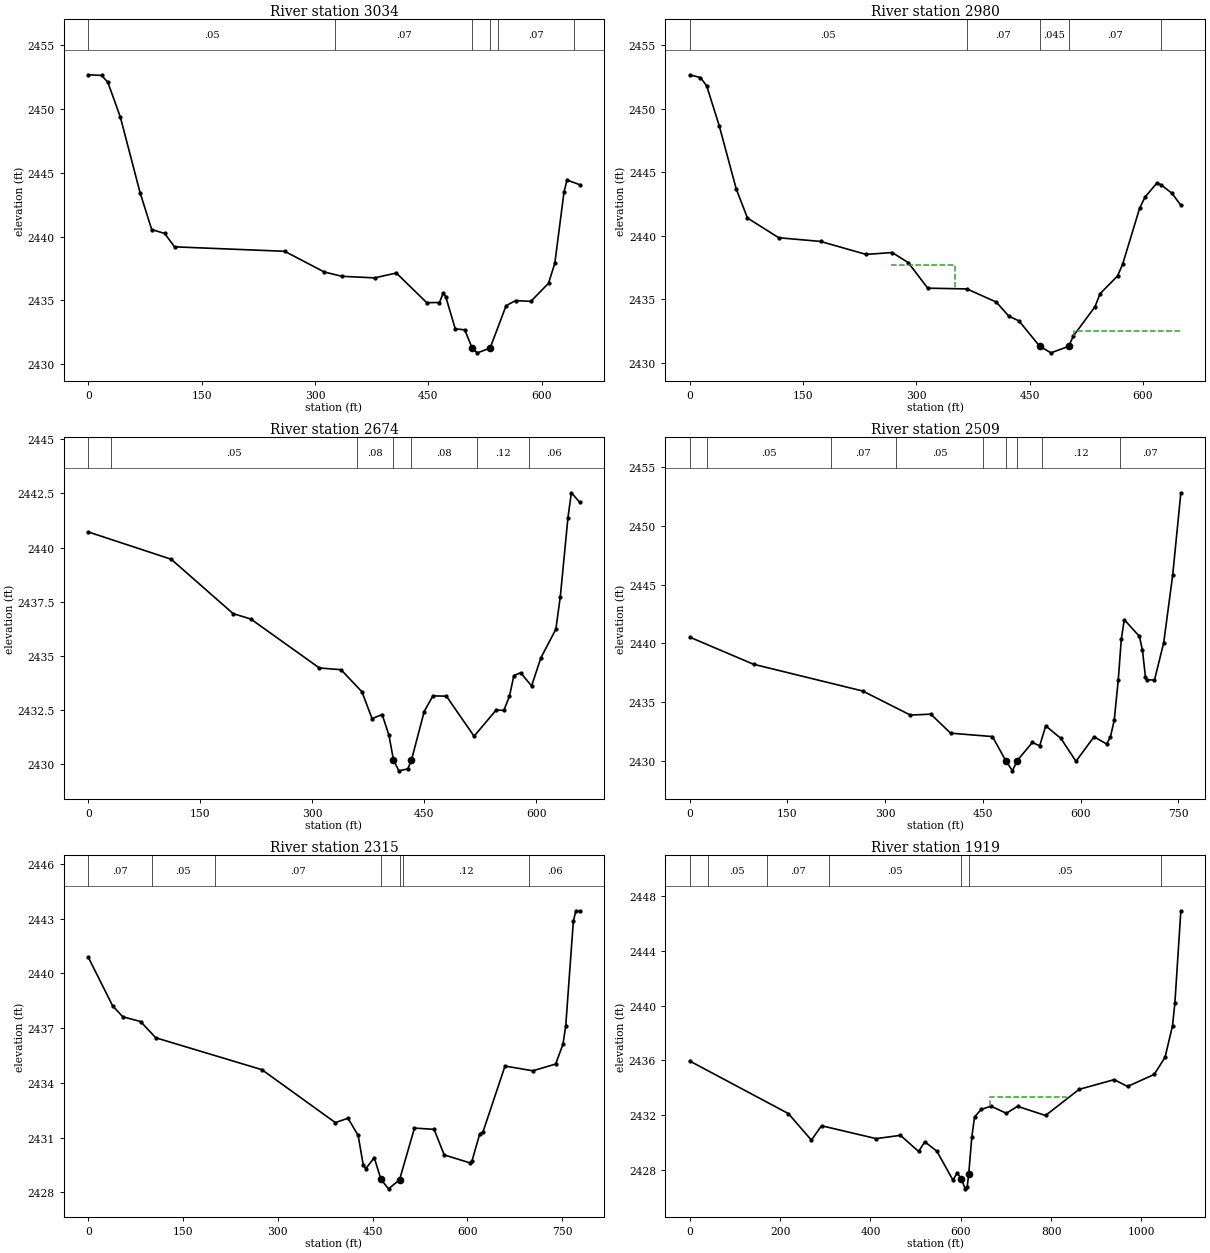
Type RM Length L Ch R = 1 ,3034    ,59.6,54.5,52
BEGIN DESCRIPTION:
structure xs 3; 20.9 ft between structure and xs
END DESCRIPTION:
XS GIS Cut Line= 6
 2268639.3831055409832.3511599962268770.68214614409796.464158018
2269064.74960488409679.0842900332269168.53811973409646.959273532
2269215.70459383409626.2236376062269252.65916491409621.806301913
#Sta/Elev= 30
       0 2452.67    17.4 2452.62    25.7 2452.09    42.3 2449.35    68.4 2443.44
    83.8 2440.55   100.9 2440.25     114  2439.2   259.8 2438.85   312.2 2437.23
   335.8 2436.89   378.9 2436.77   407.6 2437.15   447.8 2434.83   464.7 2434.84
   469.8 2435.59   473.1 2435.28   485.6 2432.78   498.2  2432.7   508.2 2431.24
     515  2430.9   531.7 2431.27   552.9 2434.59   565.4 2434.99   585.7 2434.93
   609.1 2436.35   617.4 2437.91   629.5 2443.46   633.5 2444.43   650.1 2444.07
#Mann= 6 ,-1,0
       0     .05       0  326.12     .07       0   508.2    .045       0
   531.7      .1       0  542.74     .07       0  642.91     .06       0
#XS Ineff= 2 , 0
             487  2430.9   552.6          2432.5
Permanent Ineff=
       F       F
Bank Sta=508.2,531.7
XS Rating Curve= 0 ,0
Exp/Cntr=0.5,0.3

Type RM Length L Ch R = 1 ,2980    ,304.4,306.3,304.6
BEGIN DESCRIPTION:
structure xs 2; 20.1 ft between structure and xs
END DESCRIPTION:
XS GIS Cut Line= 6
2268662.52564272409875.2107725092268793.82468336409839.323770531
 2269087.8921421409721.9439025462269191.68065695409689.818886044
2269238.84713105409669.0832501192269275.80170213409664.665914426
#Sta/Elev= 30
       0 2452.65    14.1 2452.43    22.4 2451.78      39 2448.65    61.6 2443.67
    76.4  2441.4   117.8 2439.85   173.1 2439.56   233.4 2438.54   267.9 2438.69
   289.4 2437.89     315 2435.89   366.9 2435.83   405.7  2434.8   422.4 2433.69
   435.8 2433.32   463.2 2431.33   478.2 2430.81   501.5 2431.32   507.9 2432.14
   536.5 2434.44   543.1 2435.45   566.3 2436.85   572.9 2437.75   595.6 2442.18
   602.7 2443.05   618.3 2444.14   623.7 2444.02   638.4 2443.34   650.1  2442.4
#Mann= 5 ,-1,0
       0     .05       0   366.9     .07       0   463.2    .045       0
   501.5     .07       0   623.7     .06       0
#XS Ineff= 3 ,-1
   266.2  351.77  2437.7  351.77     457  2430.9     508   650.1  2432.5
Permanent Ineff=
       F       F       F
Bank Sta=463.2,501.5
XS Rating Curve= 0 ,0
Exp/Cntr=0.5,0.3

Type RM Length L Ch R = 1 ,2674    ,165.3,164.9,163.4
BEGIN DESCRIPTION:
structure xs 1
END DESCRIPTION:
XS GIS Cut Line= 2
 2268728.2224641410195.0698599352269309.88142211409888.116841957
#Sta/Elev= 30
       0 2440.72   110.9 2439.46   193.8 2436.95   217.5  2436.7   309.3 2434.44
   338.3 2434.36   366.3 2433.34   379.9  2432.1   393.4 2432.29   402.5 2431.33
  408.572430.191   415.8 2429.69   427.7 2429.78   432.6 2430.18   449.7 2432.43
   461.3 2433.15   479.4 2433.14   516.5 2431.29   546.1  2432.5   556.3 2432.48
   563.9 2433.14   569.8 2434.09   578.9 2434.22   593.5 2433.61     606 2434.91
     626 2436.23     632 2437.74   642.2 2441.38   646.8 2442.53   657.7  2442.1
#Mann= 7 ,-1,0
       0      .1       0      30     .05       0     360     .08       0
  408.57    .045       0   432.6     .08       0     520     .12       0
     590     .06       0
Bank Sta=408.57,432.6
XS Rating Curve= 0 ,0
Exp/Cntr=0.3,0.1

Type RM Length L Ch R = 1 ,2509    ,182.3,193.9,200.3
XS GIS Cut Line= 4
2268730.48593322410213.676860694 2268737.0452225410214.988718551
2269070.25711818410201.8701399812269427.08245527409991.972882866
#Sta/Elev= 30
       0 2440.53    97.9 2438.22   265.6 2435.94   338.8 2433.89   370.2 2433.97
   400.5 2432.35   464.8 2432.06   485.2 2430.01   495.5 2429.14   502.8 2430.01
   526.1 2431.56   537.3 2431.27   546.6 2432.97     570  2431.9     593 2429.95
   620.8 2432.04   640.1 2431.43   645.9 2432.02   651.8 2433.45     658 2436.89
   662.6 2440.33   667.2 2442.02   690.4  2440.6   695.1 2439.43   699.7 2437.14
   701.5 2436.91   713.6 2436.87   727.8 2440.07   741.5 2445.79   754.1 2452.83
#Mann= 9 ,-1,0
       0      .1       0   26.69     .05       0  216.69     .07       0
  316.69     .05       0  450.16     .08       0   485.2    .045       0
   502.8     .08       0  540.16     .12       0  660.16     .07       0
Bank Sta=485.2,502.8
XS Rating Curve= 0 ,0
Exp/Cntr(USF)=0,0
Exp/Cntr=0.3,0.1

Type RM Length L Ch R = 1 ,2315    ,376.6,393,408.4
XS GIS Cut Line= 3
2268749.69443234410269.7667986842269037.87025835410284.104622281
2269525.92339366410318.700793898
#Sta/Elev= 30
       0 2440.87    38.5 2438.21    54.5 2437.62    82.6 2437.36   106.6 2436.47
   274.8 2434.72   391.1 2431.82   411.1 2432.06   427.2 2431.12   435.2 2429.51
   439.2 2429.29   452.7  2429.9   463.3 2428.71   475.3 2428.19   492.7 2428.68
   516.4 2431.52   547.5 2431.45   563.5 2430.05   603.6 2429.62   607.6 2429.73
   619.7 2431.19     625 2431.32   659.8 2434.92   703.9 2434.66     740 2435.03
   751.7 2436.13     756 2437.13     768 2442.85     772 2443.43   777.8  2443.4
#Mann= 7 ,-1,0
       0     .07       0     100     .05       0     200     .07       0
   463.3    .045       0   492.7     .07       0  498.53     .12       0
  698.53     .06       0
Bank Sta=463.3,492.7
XS Rating Curve= 0 ,0
Exp/Cntr=0.3,0.1

Type RM Length L Ch R = 1 ,1919    ,282.5,288,289.3
XS GIS Cut Line= 4
2268827.13862287410324.6695489752268970.55592105410489.167010658
2269368.89996967410689.8972734142269778.09721821 410583.02128743
#Sta/Elev= 30
       0 2435.96   218.3 2432.12   269.3 2430.18   291.7 2431.23   412.7 2430.29
   466.4 2430.53   506.7 2429.35   520.3 2430.06   547.1 2429.37   582.8 2427.25
   591.7 2427.78 601.5872427.337   609.7 2426.62   614.2 2426.76617.48652427.678
   624.5 2430.43   630.5 2431.87   644.9 2432.42   667.1 2432.66   700.8 2432.14
   725.6 2432.65   787.6 2431.98     862 2433.89   939.6  2434.6   969.1  2434.1
  1028.2 2434.98  1052.2 2436.23  1068.7 2438.54    1074 2440.21  1087.2 2446.94
#Mann= 7 ,-1,0
       0     .07       0      40     .05       0     170     .07       0
  308.24     .05       0 601.587    .045       0617.4865     .05       0
  1044.3     .06       0
#XS Ineff= 1 ,-1
  665.35   832.4 2433.33
Permanent Ineff=
       F
Bank Sta=601.587,617.4865
XS Rating Curve= 0 ,0
Exp/Cntr(USF)=0,0
Exp/Cntr=0.3,0.1

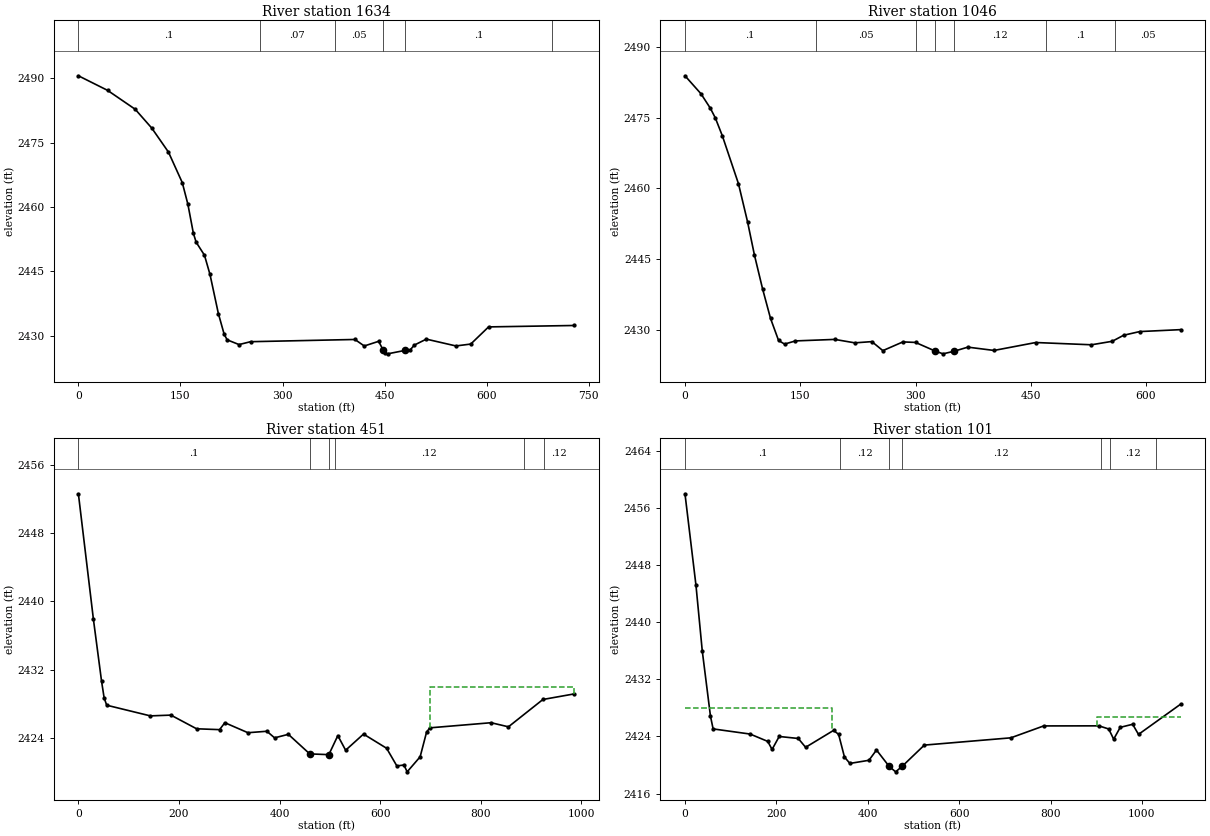
Type RM Length L Ch R = 1 ,1634    ,580.3,588.2,591
XS GIS Cut Line= 3
2268694.17483631410813.9155908162268897.09188105410775.152023478
2269375.27335143410984.138444166
#Sta/Elev= 30
       0 2490.56    42.8 2487.17    83.5 2482.75   107.9 2478.35   132.4 2472.76
   152.7 2465.64   160.9 2460.62     169 2453.82   173.1 2451.75   185.3 2448.72
   193.4 2444.24   205.7 2435.13   214.3 2430.26   218.7 2428.99   236.1 2427.89
     253 2428.56   406.4 2429.08   420.1 2427.56   441.3 2428.65   447.4 2426.74
     450 2425.84   454.4 2425.73     480 2426.53   486.9 2426.51   493.7 2427.77
   511.3 2429.16   554.8 2427.57   576.6 2428.01   602.8 2432.01   728.4 2432.34
#Mann= 6 ,-1,0
       0      .1       0  266.59     .07       0  376.59     .05       0
   447.4    .045       0     480      .1       0  696.59     .05       0
Bank Sta=447.4,480
XS Rating Curve= 0 ,0
Exp/Cntr(USF)=0,0
Exp/Cntr=0.3,0.1

Type RM Length L Ch R = 1 ,1046    ,594.1,594.8,594.2
XS GIS Cut Line= 2
2268622.87946484411031.8245816812269117.01814761411446.350233059
#Sta/Elev= 30
       0 2483.86    20.8 2480.05      33 2476.98    39.5 2474.92    48.7  2471.1
    69.6 2460.98    81.4 2452.92    90.4 2445.85   100.9 2438.74   111.3 2432.43
   121.8 2427.74   129.6 2426.98   143.8 2427.65   194.9 2427.97     221 2427.24
   243.2  2427.5   257.5 2425.59   283.6 2427.44     300 2427.33   325.22425.527
   335.8 2424.91   350.12425.457   368.1 2426.33   402.2 2425.63   456.4 2427.31
     529 2426.83     556 2427.57   570.8 2428.85   591.7 2429.63     645 2430.04
#Mann= 7 ,-1,0
       0      .1       0     170     .05       0     300     .12       0
   325.2    .045       0   350.1     .12       0     470      .1       0
     560     .05       0
Bank Sta=325.2,350.1
XS Rating Curve= 0 ,0
Exp/Cntr(USF)=0,0
Exp/Cntr=0.3,0.1

Type RM Length L Ch R = 1 ,451     ,350.1,350.1,350.1
XS GIS Cut Line= 3
2268152.07564007411410.5601029432268705.18006397411849.700959856
2268934.48182397411689.730602998
#Sta/Elev= 30
       0 2452.58    29.9 2437.88    46.1 2430.63    51.2 2428.69    56.3 2427.83
   143.1 2426.58     184 2426.67   235.1 2425.07   280.8 2424.97   291.3 2425.78
   337.2 2424.61   374.9 2424.78   390.2 2424.01   417.6 2424.42460.09892422.131
498.09882422.042     516 2424.27   531.5 2422.56   567.1 2424.45     613 2422.79
   633.4 2420.72   647.5 2420.83   653.9 2420.03   679.7 2421.79   692.5 2424.68
     699 2425.18   820.8 2425.78   855.3  2425.3   923.9  2428.5   985.8 2429.15
#Mann= 6 ,-1,0
       0      .1       0460.0989    .045       0498.0988      .1       0
     510     .12       0  886.24     .06       0  926.24     .12       0
#XS Ineff= 2 , 0
                             700            2430
Permanent Ineff=
       F       F
Bank Sta=460.0989,498.0988
XS Rating Curve= 0 ,0
Exp/Cntr(USF)=0,0
Exp/Cntr=0.3,0.1

Type RM Length L Ch R = 1 ,101     ,,,
XS GIS Cut Line= 4
 2267980.4938017411795.573008536 2268269.2534809411983.894538445
2268465.06898552412045.1842154952268894.64162771411726.645655516
#Sta/Elev= 30
       0 2458.04    24.1 2445.18    37.8 2436.02    55.8 2426.84    61.6 2425.06
   142.6 2424.34   181.1 2423.31   190.6 2422.18   206.2    2424   247.9 2423.72
     264 2422.48   325.1 2424.85   336.2  2424.3     349 2421.12   360.9 2420.22
   402.6 2420.66   419.1  2422.1446.99152419.793     461 2419.04474.98912419.795
   523.8 2422.79   713.1 2423.81     785 2425.48   905.9 2425.49   927.3 2425.05
   938.2 2423.62   952.5 2425.28   979.7 2425.71   992.5 2424.29  1084.7 2428.53
#Mann= 7 ,-1,0
       0      .1       0     340     .12       0446.9915    .045       0
474.9891     .12       0  909.93     .07       0  929.93     .12       0
 1029.93     .06       0
#XS Ineff= 2 , 0
           321.8 2427.96  901.86         2426.76
Permanent Ineff=
       F       F
Bank Sta=446.9915,474.9891
XS Rating Curve= 0 ,0
Exp/Cntr(USF)=0,0
Exp/Cntr=0.3,0.1
LCMann Table=0

Chan Stop Cuts=-1
Use User Specified Reach Order=0
Composite Channel Slope=5